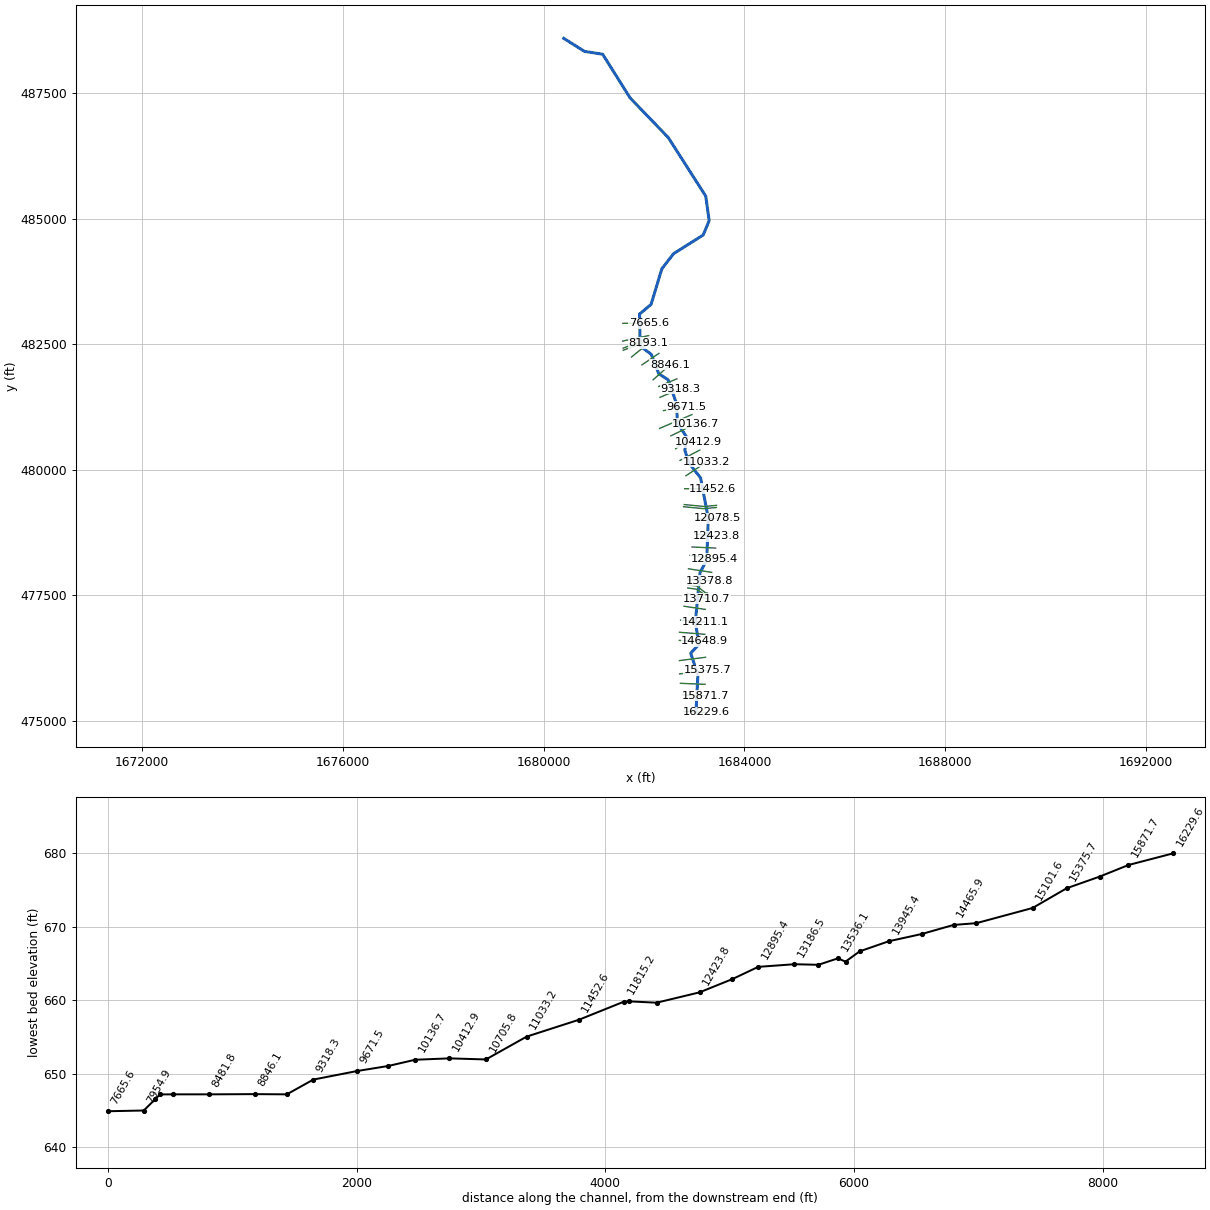
--- ClymerCk.prj (project) ---

Proj Title=ClymerCk
Current Plan=p01
Default Exp/Contr=0,0
English Units
Geom File=g01
Flow File=f01
Plan File=p01
BEGIN DESCRIPTION:
AMEC Environment & Infrastructure, 2013
Projection: NAD 1983 State Plane West Virginia South FIPS 4702 (US Feet)
Vertical Datum: NAVD 1988
END DESCRIPTION:
DSS Export Rating Curves= 0
DSS Export Rating Curve Sorted= 0
DSS Export Volume Flow Curves= 0
DXF OffsetX= 0
DXF OffsetY= 0
DXF ScaleX= 0
DXF ScaleY= 0

--- ClymerCk.p01 (plan) ---

Plan Title=Floodplain
Program Version=4.00
Geom File=g01
Flow File=f01
K Sum by GR=0
Std Step Tol=0.01
Critical Tol=0.01
Num of Std Step Trials=20
Max Error Tol=0.3
Flow Tol Ratio=0.001
Split Flow NTrial=30
Split Flow Tol=0.02
Split Flow Ratio=0.02
Log Output Level=0
Friction Slope Method=1
Unsteady Friction Slope Method=2
Unsteady Bridges Friction Slope Method=1
Global Log Level=0
CheckData=False
Run HTab=0
Run UNet=0
Run PostProcess=0
UNET Theta=0
UNET Theta Warmup=0
UNET ZTol=0
UNET ZSATol=0
UNET MxIter=0
UNET MaxInSteps=0
UNET DtIC=0
UNET DtMin=0
UNET MaxCRTS=0
UNET WFStab=0
UNET SFStab=0
UNET WFX=0
UNET SFX=0
UNET DSS MLevel=0
UNET DZMax Abort=0
UNET Convert EG Bridges=0
UNET Use Existing IB Tables=0
UNET Froude Limit=0
UNET Froude Power=0
Write IC File=0
Echo Input=False
Echo Output=False
Write Detailed=0

--- ClymerCk.f01 (steady flow) ---

Flow Title=USGS Regress. Eqn. (2010) - Western-Plateaus
Program Version=4.10
Number of Profiles= 1
Profile Names=P100yr
River Rch & RM=ClymerCk,Main            ,16229.6
     891
River Rch & RM=ClymerCk,Main            ,15640.2
     911
River Rch & RM=ClymerCk,Main            ,14648.9
     996
River Rch & RM=ClymerCk,Main            ,12078.5
    1111
River Rch & RM=ClymerCk,Main            ,10136.7
    1280
River Rch & RM=ClymerCk,Main            ,8481.8
    1338
River Rch & RM=ClymerCk,Main            ,7597.4
    1485
River Rch & RM=ClymerCk,Main            ,6685.3
    1496
River Rch & RM=ClymerCk,Main            ,5780.5
    1542
River Rch & RM=ClymerCk,Main            ,2697.9
    1710
River Rch & RM=ClymerCk,Main            ,212.1
    1781
Boundary for River Rch & Prof#=ClymerCk,Main            , 1
Up Type= 0
Dn Type= 3
Dn Slope=0.001
DSS Import GetInterval= 0
DSS Import GetPeak= 0
DSS Import FillOption= 0

--- ClymerCk.g01 (geometry) ---

Geom Title=USGS 3m DEM
Program Version=4.10

River Reach=ClymerCk        ,Main
Reach XY= 30
     1683034.963      475152.772     1683073.734      475919.415
     1682930.505      476350.404     1683098.474      476531.394
     1683021.651      476962.383     1683116.703      477959.779
     1683249.515      478201.967     1683280.765      479037.904
      1683127.12      479842.592     1682897.953      480131.654
     1682813.317      480393.373     1682853.682      480647.279
     1682666.182       480935.04     1682647.953      481319.154
     1682482.588      481793.113     1682293.786       481916.81
     1682145.349      482299.623     1681922.692      482467.592
     1681910.974      483103.008     1682141.442      483297.019
     1682354.984       484004.05     1682590.661      484307.435
     1683180.505      484678.529     1683297.692      484964.988
     1683229.984      485451.967      1682483.89      486617.331
     1681722.172      487408.998     1681176.599      488277.488
     1680815.922      488333.477      1680399.89      488593.899

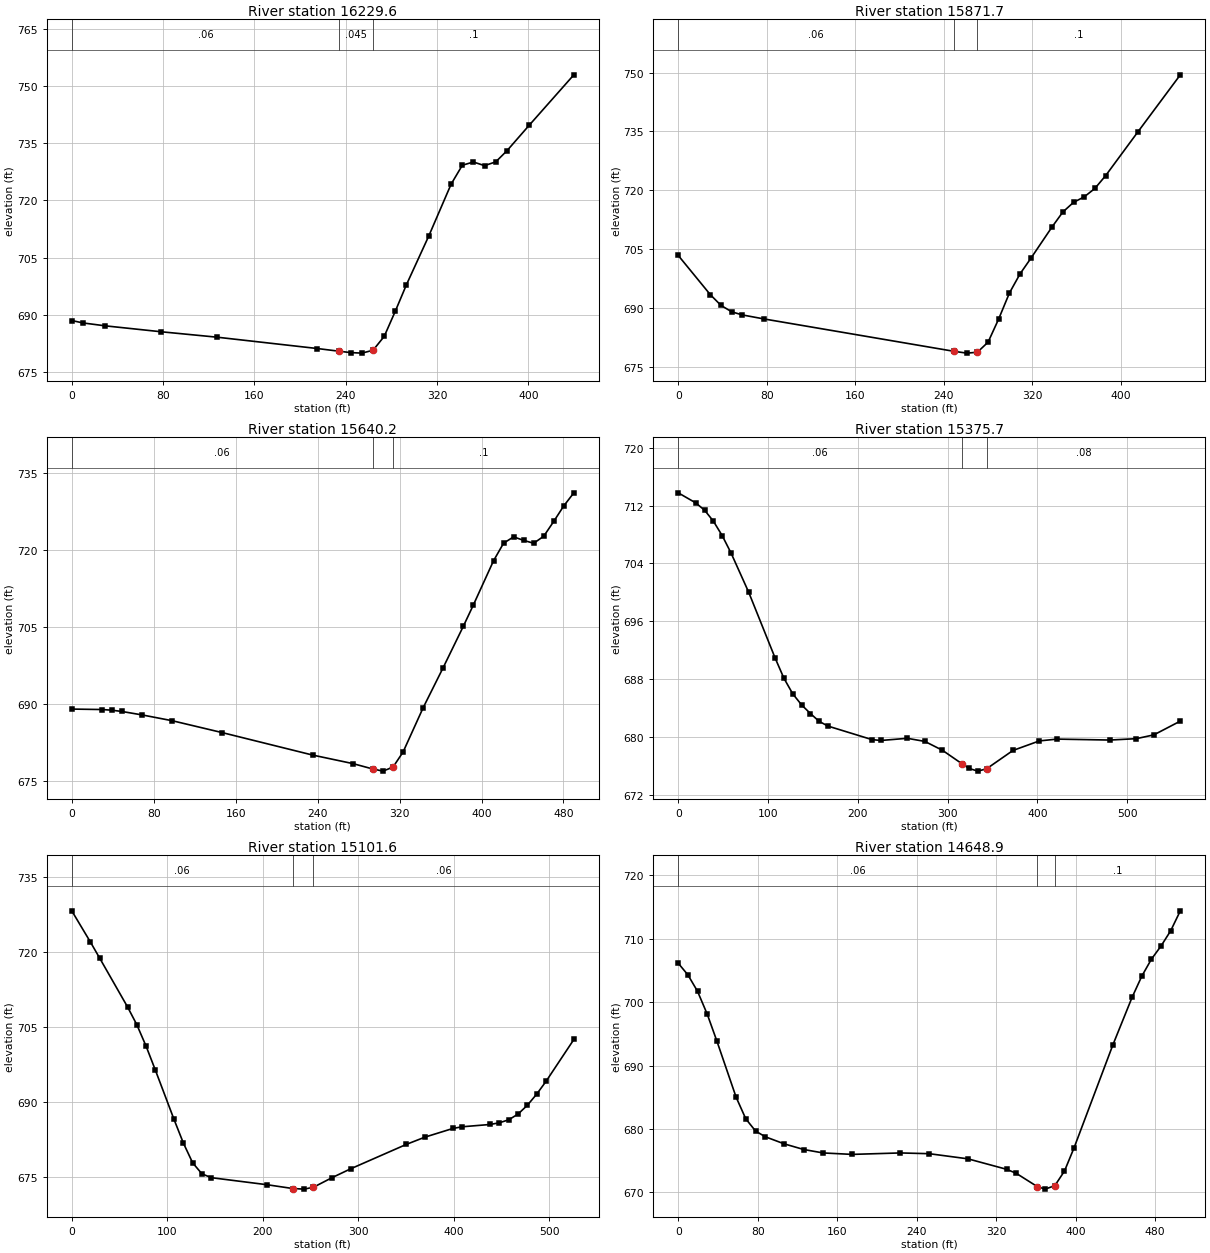
Type RM Length L Ch R = 1 ,16229.6 ,358.4,357.9,356.8
XS GIS Cut Line= 2
     1682798.376      475192.743     1683237.708      475172.174
#Sta/Elev= 22
       0  688.55     9.8  687.92    29.3  687.16    78.2  685.61   127.1  684.19
     215  681.22   234.3   680.5   244.3  680.15   254.1  680.01   263.9  680.76
   273.7   684.4   283.4  690.99   293.2  697.96   312.8  710.75   332.3  724.28
   342.1  729.23   351.8  730.08   361.6  729.13   371.4  730.12   381.2  733.03
   400.7  739.71   439.8  752.92
#Mann= 3 , 0 , 0
       0     .06       0   234.3    .045       0   263.9      .1       0
Bank Sta=234.3,263.9
XS Rating Curve= 0 ,0
Exp/Cntr=0.3,0.1

Type RM Length L Ch R = 1 ,15871.7 ,230.2,231.5,232.1
XS GIS Cut Line= 2
     1682763.053      475522.917     1683216.301      475501.696
#Sta/Elev= 22
       0  703.36      29  693.35    38.6  690.62    48.3  688.98    57.9  688.18
    77.2  687.17   248.8  678.91   260.7  678.43   270.3  678.65     280  681.24
   289.6  687.17   299.3  693.79   308.9  698.67   318.6  702.61   337.9  710.68
   347.6  714.46   357.2  716.91   366.9  718.32   376.5  720.46   386.2  723.72
   415.1   734.8   453.7  749.46
#Mann= 3 , 0 , 0
       0     .06       0   248.8    .045       0   270.3      .1       0
Bank Sta=248.8,270.3
XS Rating Curve= 0 ,0
Exp/Cntr=0.3,0.1

Type RM Length L Ch R = 1 ,15640.2 ,261.6,264.6,266.5
XS GIS Cut Line= 2
     1682725.826      475750.888     1683215.507      475731.478
#Sta/Elev= 26
       0  688.96    29.4  688.87    39.2  688.74      49  688.49    68.6  687.82
      98  686.69     147  684.36   235.2  679.98   274.4  678.32   293.8  677.27
   303.8  676.85   313.6  677.64   323.4  680.58     343  689.22   362.6  697.07
   382.2  705.11     392  709.27   411.7   717.9   421.5  721.33   431.3  722.57
   441.1  721.88   450.9  721.32   460.7  722.69   470.5  725.59   480.3  728.62
   490.1  731.16
#Mann= 3 , 0 , 0
       0     .06       0   293.8    .045       0   313.6      .1       0
Bank Sta=293.8,313.6
XS Rating Curve= 0 ,0
Exp/Cntr=0.3,0.1

Type RM Length L Ch R = 1 ,15375.7 ,273.9,274.1,275.3
XS GIS Cut Line= 2
     1682709.001      475938.353     1683263.757      476008.962
#Sta/Elev= 30
       0  713.77    19.6  712.37    29.4  711.36    39.2  709.84    49.1  707.82
    58.9  705.42    78.5  700.01   107.9  690.92   117.7  688.12   127.5  685.97
   137.4  684.43   147.2  683.24     157  682.15   166.8   681.5   215.8  679.63
   225.6  679.51   255.1  679.81   274.7  679.38   294.3  678.15     316  676.29
   323.8  675.65   333.6  675.27   343.4  675.59   372.8  678.13   402.2  679.45
   421.9   679.7   480.7  679.57   510.2  679.76   529.8  680.29   559.2  682.19
#Mann= 3 , 0 , 0
       0     .06       0     316    .045       0   343.4     .08       0
Bank Sta=316,343.4
XS Rating Curve= 0 ,0
Exp/Cntr=0.3,0.1

Type RM Length L Ch R = 1 ,15101.6 ,446.9,452.6,450.4
XS GIS Cut Line= 2
     1682705.253      476203.871     1683226.536       476270.22
#Sta/Elev= 30
       0  728.19    19.5  721.96    29.2  718.74    58.4  708.98    68.1  705.43
    77.8  701.14    87.6  696.31     107  686.52   116.8  681.79   126.5  677.84
   136.2  675.64     146  674.87   204.4  673.46   231.3   672.7   243.3  672.58
     253  672.96   272.5  674.88   291.9  676.64   350.3  681.53   369.8  682.98
     399  684.71   408.7  685.04   437.9   685.5   447.6  685.84   457.4  686.44
   467.1  687.58   476.8  689.33   486.6  691.56   496.3  694.09   525.5  702.48
#Mann= 3 , 0 , 0
       0     .06       0   231.3    .045       0     253     .06       0
Bank Sta=231.3,253
XS Rating Curve= 0 ,0
Exp/Cntr=0.3,0.1

Type RM Length L Ch R = 1 ,14648.9 ,183.4,183,182.2
XS GIS Cut Line= 2
     1682704.257      476605.883     1683209.299      476586.235
#Sta/Elev= 30
       0  706.15     9.7  704.32    19.4  701.73    29.2  698.11    38.9  693.87
    58.3     685      68   681.6    77.8  679.68    87.5  678.78   106.9  677.64
   126.4  676.76   145.8  676.22     175  675.99   223.6  676.22   252.7   676.1
   291.6  675.29   330.5  673.64   340.2  673.01   361.3  670.92   369.4  670.51
   379.1  671.06   388.8  673.36   398.5  677.05   437.4  693.22   456.8  700.75
   466.6   704.1   476.3  706.79     486  708.87   495.7  711.27   505.4  714.42
#Mann= 3 , 0 , 0
       0     .06       0   361.3    .045       0   379.1      .1       0
Bank Sta=361.3,379.1
XS Rating Curve= 0 ,0
Exp/Cntr=0.3,0.1

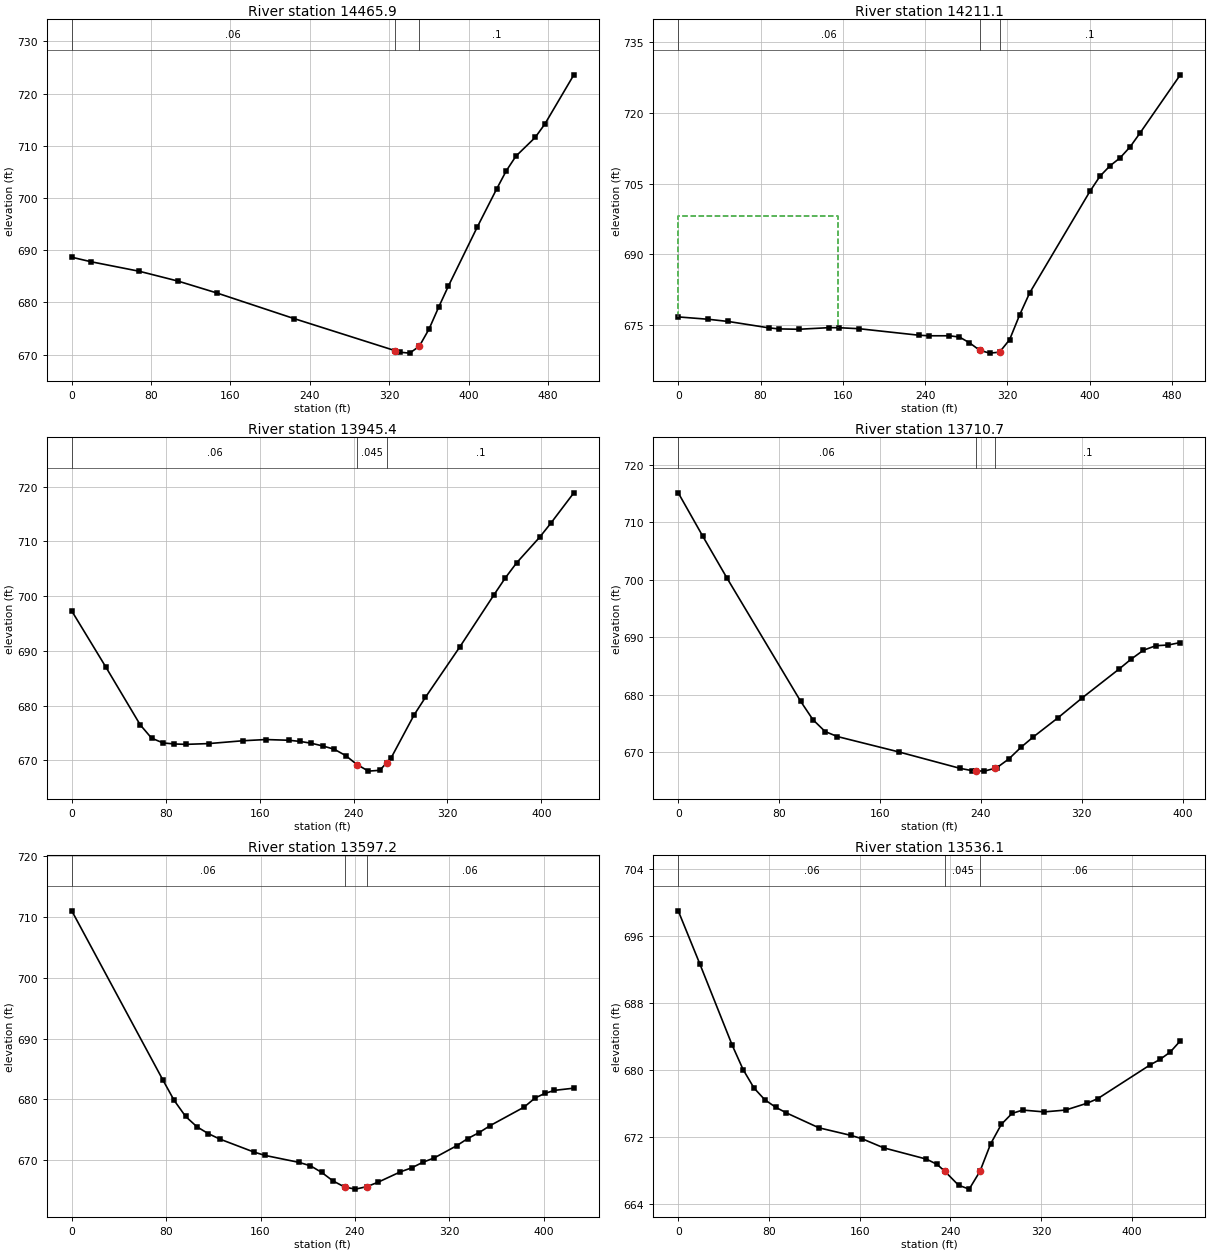
Type RM Length L Ch R = 1 ,14465.9 ,254.5,254.8,254.8
XS GIS Cut Line= 2
     1682707.246      476767.528     1683211.845      476727.763
#Sta/Elev= 20
       0  688.64    19.5  687.77    68.1  685.95   107.1  684.07     146  681.81
   223.9   676.9   325.7  670.76     331  670.44   340.7  670.27   350.4  671.59
   360.2  674.88   369.9  679.07   379.6  683.07   408.8  694.41   428.3  701.69
     438  705.17   447.8     708   467.2  711.58     477  714.16   506.2  723.58
#Mann= 3 , 0 , 0
       0     .06       0   325.7    .045       0   350.4      .1       0
Bank Sta=325.7,350.4
XS Rating Curve= 0 ,0
Exp/Cntr=0.3,0.1

Type RM Length L Ch R = 1 ,14211.1 ,267.3,265.7,264
XS GIS Cut Line= 2
     1682729.547      477009.442     1683216.222      476971.089
#Sta/Elev= 27
       0  676.72    29.3  676.22    48.8  675.75    87.9  674.41    97.6  674.18
   117.2   674.1   146.5  674.44   156.2  674.43   175.8  674.22   234.3  672.83
   244.1  672.72   263.6  672.72   273.4  672.46   283.2  671.23   293.1  669.65
   302.7  669.04   312.4  669.24   322.2  671.89     332  677.16   341.7  681.81
   400.3  703.35   410.1  706.57   419.8  708.76   429.6  710.45   439.4  712.79
   449.1  715.75   488.2  728.07
#Mann= 3 , 0 , 0
       0     .06       0   293.1    .045       0   312.4      .1       0
#XS Ineff= 2 , 0
          155.03  698.12
Permanent Ineff=
       F       F
Bank Sta=293.1,312.4
XS Rating Curve= 0 ,0
Exp/Cntr=0.3,0.1

Type RM Length L Ch R = 1 ,13945.4 ,237.1,234.8,232.3
XS GIS Cut Line= 2
     1682797.788       477286.23     1683220.752      477222.874
#Sta/Elev= 30
       0   697.3    29.2     687    58.3  676.51      68  674.07    77.8   673.2
    87.5  673.01    97.2  672.94   116.6  673.08   145.8   673.6   165.2  673.82
   184.7  673.69   194.4  673.48   204.1  673.14   213.8  672.65   223.6  672.05
   233.3  670.89     243  669.25   252.7  668.05   262.4   668.2   268.3   669.6
   272.2  670.53   291.6  678.31   301.3  681.54   330.5  690.72   359.6  700.24
   369.4  703.37   379.1  706.14   398.5  710.76   408.2  713.37   427.7  718.89
#Mann= 3 , 0 , 0
       0     .06       0     243    .045       0   268.3      .1       0
Bank Sta=243,268.3
XS Rating Curve= 0 ,0
Exp/Cntr=0.3,0.1

Type RM Length L Ch R = 1 ,13710.7 ,123.8,113.4,101.7
XS GIS Cut Line= 2
      1682860.18      477539.296     1683245.537      477439.028
#Sta/Elev= 25
       0  715.11    19.4  707.58    38.8  700.22    97.1  678.82   106.8  675.63
   116.5  673.56   126.2  672.69   174.8  670.02   223.4  667.16   233.1  666.75
   235.9  666.73   242.8  666.67   250.9  667.15   252.5  667.24   262.2  668.79
   271.9  670.83   281.6  672.62   301.1  675.94   320.5  679.44   349.6  684.43
   359.3  686.18     369  687.72   378.8   688.5   388.5  688.62   398.2  689.05
#Mann= 3 , 0 , 0
       0     .06       0   235.9    .045       0   250.9      .1       0
Bank Sta=235.9,250.9
XS Rating Curve= 0 ,0
Exp/Cntr=0.3,0.1

Type RM Length L Ch R = 1 ,13597.2 ,60.8,61.1,62.8
XS GIS Cut Line= 4
     1682870.004       477649.42     1683042.143      477626.302
     1683225.552      477506.389     1683257.852       477501.68
#Sta/Elev= 30
       0     711    77.2  683.21    86.8  679.84    96.5  677.21   106.1  675.51
   115.8  674.38   125.4   673.5   154.4  671.36     164   670.8   192.7  669.66
   202.3   669.1   211.8  668.02   221.3  666.63   231.4   665.6   240.4  665.27
   249.9  665.67   259.4  666.39   278.5  668.11     288  668.76   297.5  669.68
   307.1  670.39   326.1  672.39   335.6  673.58   345.2  674.56   354.7  675.72
   383.3  678.74   392.8  680.27     401     681   409.1   681.5   425.5  681.86
#Mann= 3 , 0 , 0
       0     .06       0   231.4    .045       0   249.9     .06       0
Bank Sta=231.4,249.9
XS Rating Curve= 0 ,0
Exp/Cntr=0.3,0.1

Type RM Length L Ch R = 1 ,13536.1 ,142.6,157.3,171.4
XS GIS Cut Line= 4
     1682872.468      477709.427     1683052.505      477689.209
     1683222.781      477554.697     1683266.904      477547.738
#Sta/Elev= 30
       0  699.02    19.1  692.65    47.7  682.91    57.2  680.03    66.8  677.82
    76.3  676.42    85.8  675.53    95.4  674.84     124  673.06   152.6  672.14
   162.1  671.75   181.2  670.66   218.9  669.31   228.3  668.68   235.3  667.83
   247.2  666.19   256.6  665.72   266.1  667.85   275.5  671.13     285  673.48
   294.4  674.78   303.8  675.18   322.7  674.96   341.6  675.18   360.4  675.99
   369.9  676.54     416  680.57     425  681.25   433.9  682.12   442.8  683.46
#Mann= 3 , 0 , 0
       0     .06       0   235.3    .045       0   266.1     .06       0
Bank Sta=235.3,266.1
XS Rating Curve= 0 ,0
Exp/Cntr=0.3,0.1

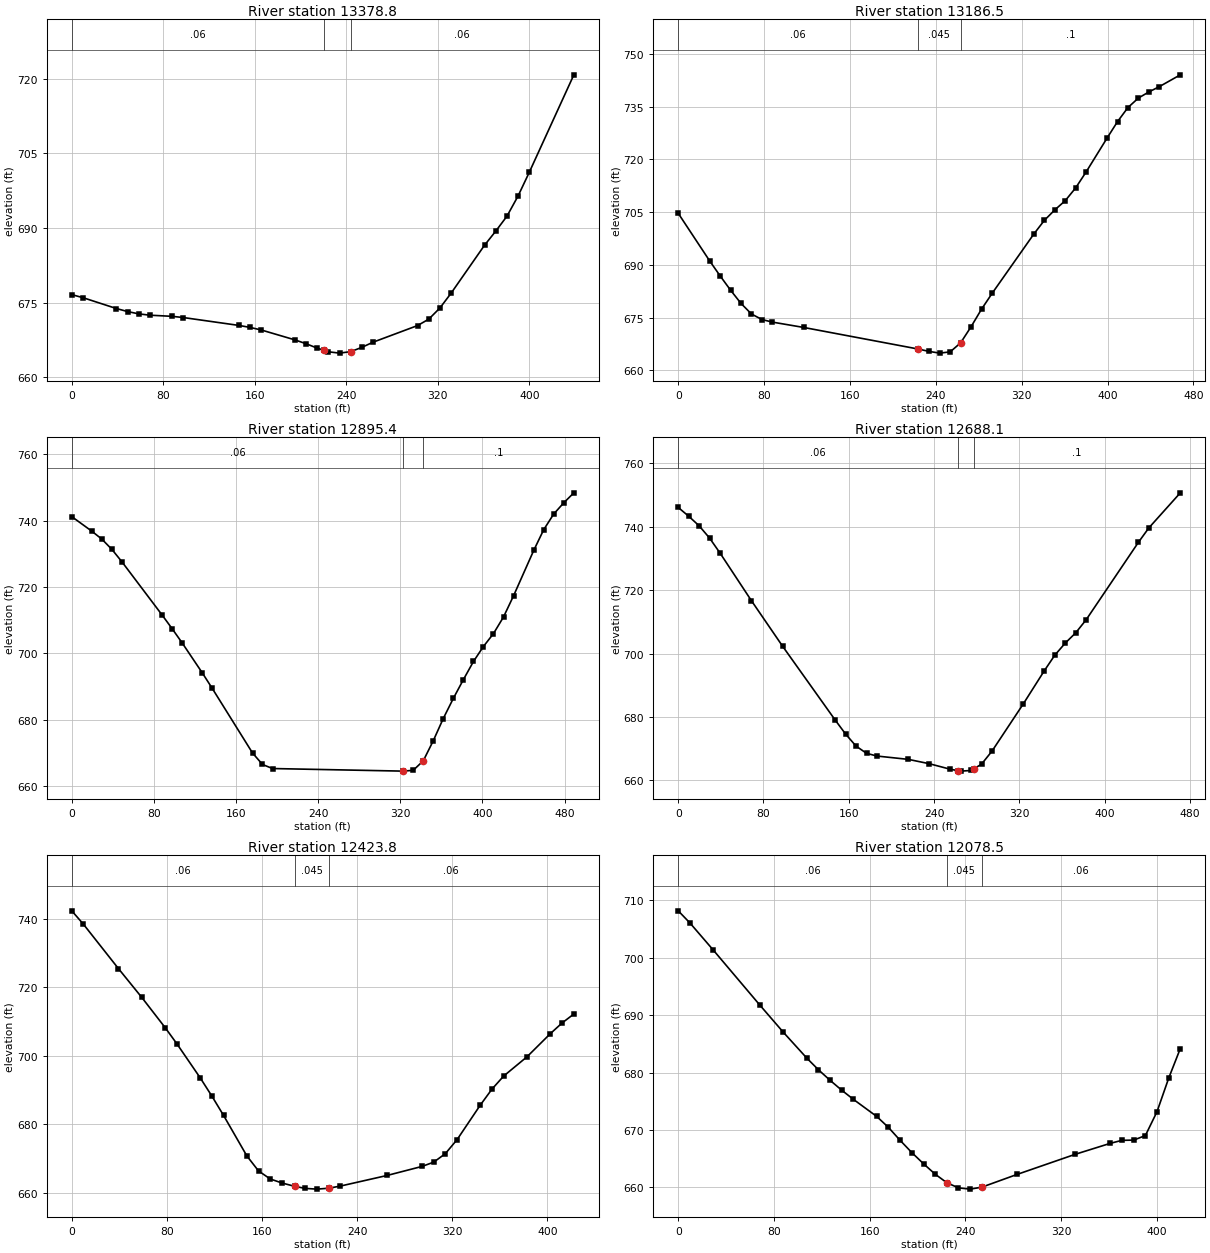
Type RM Length L Ch R = 1 ,13378.8 ,194.6,192.3,190.5
XS GIS Cut Line= 2
     1682876.955      477818.679     1683315.065      477792.766
#Sta/Elev= 30
       0  676.59     9.8  675.98      39   673.8    48.8  673.19    58.5  672.73
    68.3  672.46    87.8  672.23    97.5  671.99   146.3   670.4     156     670
   165.8  669.48   195.1   667.5   204.8  666.73   214.6  665.84   220.9  665.37
   224.3  665.11   234.1  664.84   243.8  665.14   253.6     666   263.3  667.03
   302.3  670.38   312.1  671.67   321.8   673.9   331.6  676.88   360.8  686.51
   370.6  689.34   380.4  692.34   390.1  696.39   399.9  701.15   438.9  720.75
#Mann= 3 , 0 , 0
       0     .06       0   220.9    .045       0   243.8     .06       0
Bank Sta=220.9,243.8
XS Rating Curve= 0 ,0
Exp/Cntr=0.3,0.1

Type RM Length L Ch R = 1 ,13186.5 ,291.1,291.1,290.8
XS GIS Cut Line= 2
      1682885.69       478031.39     1683348.127      477960.978
#Sta/Elev= 30
       0  704.67    29.2  691.18      39  686.89    48.7  682.84    58.5  679.05
    68.2  676.05      78  674.47    87.7  673.74   116.9  672.22     223 666.118
   233.9   665.4   243.6  664.92   253.4  665.28   263.1  667.84   272.9  672.45
   282.6  677.42   292.4  681.89   331.3  698.77   341.1  702.66   350.8  705.62
   360.6  708.27   370.3   711.9   380.1  716.46   399.6  726.08   409.3  730.74
     419  734.74   428.8  737.45   438.5  739.17   448.3  740.69   467.8  744.04
#Mann= 3 , 0 , 0
       0     .06       0     223    .045       0   263.1      .1       0
Bank Sta=223,263.1
XS Rating Curve= 0 ,0
Exp/Cntr=0.3,0.1

Type RM Length L Ch R = 1 ,12895.4 ,205.3,207.3,209.4
XS GIS Cut Line= 2
     1682916.838      478300.296     1683400.349      478226.675
#Sta/Elev= 30
       0  741.21    19.6  736.81    29.4  734.41    39.1  731.34    48.9  727.59
      88  711.58    97.8  707.44   107.6  703.15   127.2  694.13   136.9  689.45
   176.1  670.02   185.8  666.56   195.6  665.34   322.8  664.56   332.6   664.8
   342.4  667.66   352.1  673.68   361.9  680.41   371.7  686.47   381.5  692.12
   391.3  697.58     401  702.09   410.8  705.98   420.6     711   430.4  717.39
     450  731.02   459.7  737.26   469.5     742   479.3  745.38   489.1  748.38
#Mann= 3 , 0 , 0
       0     .06       0   322.8    .045       0   342.4      .1       0
Bank Sta=322.8,342.4
XS Rating Curve= 0 ,0
Exp/Cntr=0.3,0.1

Type RM Length L Ch R = 1 ,12688.1 ,265.9,264.3,262
XS GIS Cut Line= 2
     1682956.522      478466.057       1683427.1      478444.026
#Sta/Elev= 30
       0  746.12     9.8  743.36    19.6  740.33    29.4  736.46    39.3  731.69
    68.7  716.68    98.1  702.24   147.2  679.05     157  674.62   166.8  670.81
   176.7  668.52   186.5  667.66   215.9  666.61   235.6  665.24   255.2   663.5
   262.4  663.06     265   662.9   274.8   663.1   277.4  663.63   284.6  665.11
   294.4  669.21   323.9  684.19   343.5  694.59   353.3  699.48   363.1   703.3
     373  706.57   382.8   710.7   431.8  735.13   441.6  739.68   471.1  750.74
#Mann= 3 , 0 , 0
       0     .06       0   262.4    .045       0   277.4      .1       0
Bank Sta=262.4,277.4
XS Rating Curve= 0 ,0
Exp/Cntr=0.3,0.1

Type RM Length L Ch R = 1 ,12423.8 ,340.8,345.3,350.2
XS GIS Cut Line= 2
     1683017.996      478722.838     1683437.907      478678.328
#Sta/Elev= 30
       0  742.35     9.8  738.44    39.3  725.46    58.9  717.06    78.6  708.22
    88.4  703.53     108   693.6   117.8  688.28   127.7   682.6   147.3  670.77
   157.1   666.4   166.9  664.06   176.8  662.88   187.6   661.9   196.4   661.3
   206.2  661.09     216  661.35   225.9  661.98   265.1  665.07   294.6  667.72
   304.4  668.96   314.2  671.44   324.1  675.55   343.7  685.67   353.5  690.32
   363.3  694.11     383  699.76   402.6  706.51   412.4   709.6   422.3  712.22
#Mann= 3 , 0 , 0
       0     .06       0   187.6    .045       0     216     .06       0
Bank Sta=187.6,216
XS Rating Curve= 0 ,0
Exp/Cntr=0.3,0.1

Type RM Length L Ch R = 1 ,12078.5 ,218.3,218.7,219
XS GIS Cut Line= 2
     1683035.846      479009.051     1683454.497      479038.012
#Sta/Elev= 29
       0  708.17     9.8  706.05    29.3  701.33    68.3  691.72    87.8  687.02
   107.4  682.52   117.1  680.49   126.9  678.64   136.6  676.92   146.4  675.32
   165.9  672.34   175.7  670.43   185.4  668.19   195.2  666.05     205   664.1
   214.7  662.29   224.5  660.79   234.2   659.9     244  659.68   253.7  660.02
     283  662.23   331.8  665.75   361.1  667.66   370.8  668.18   380.6  668.22
   390.4  669.01   400.1  673.16   409.9  679.02   419.6  684.18
#Mann= 3 , 0 , 0
       0     .06       0   224.5    .045       0   253.7     .06       0
Bank Sta=224.5,253.7
XS Rating Curve= 0 ,0
Exp/Cntr=0.3,0.1

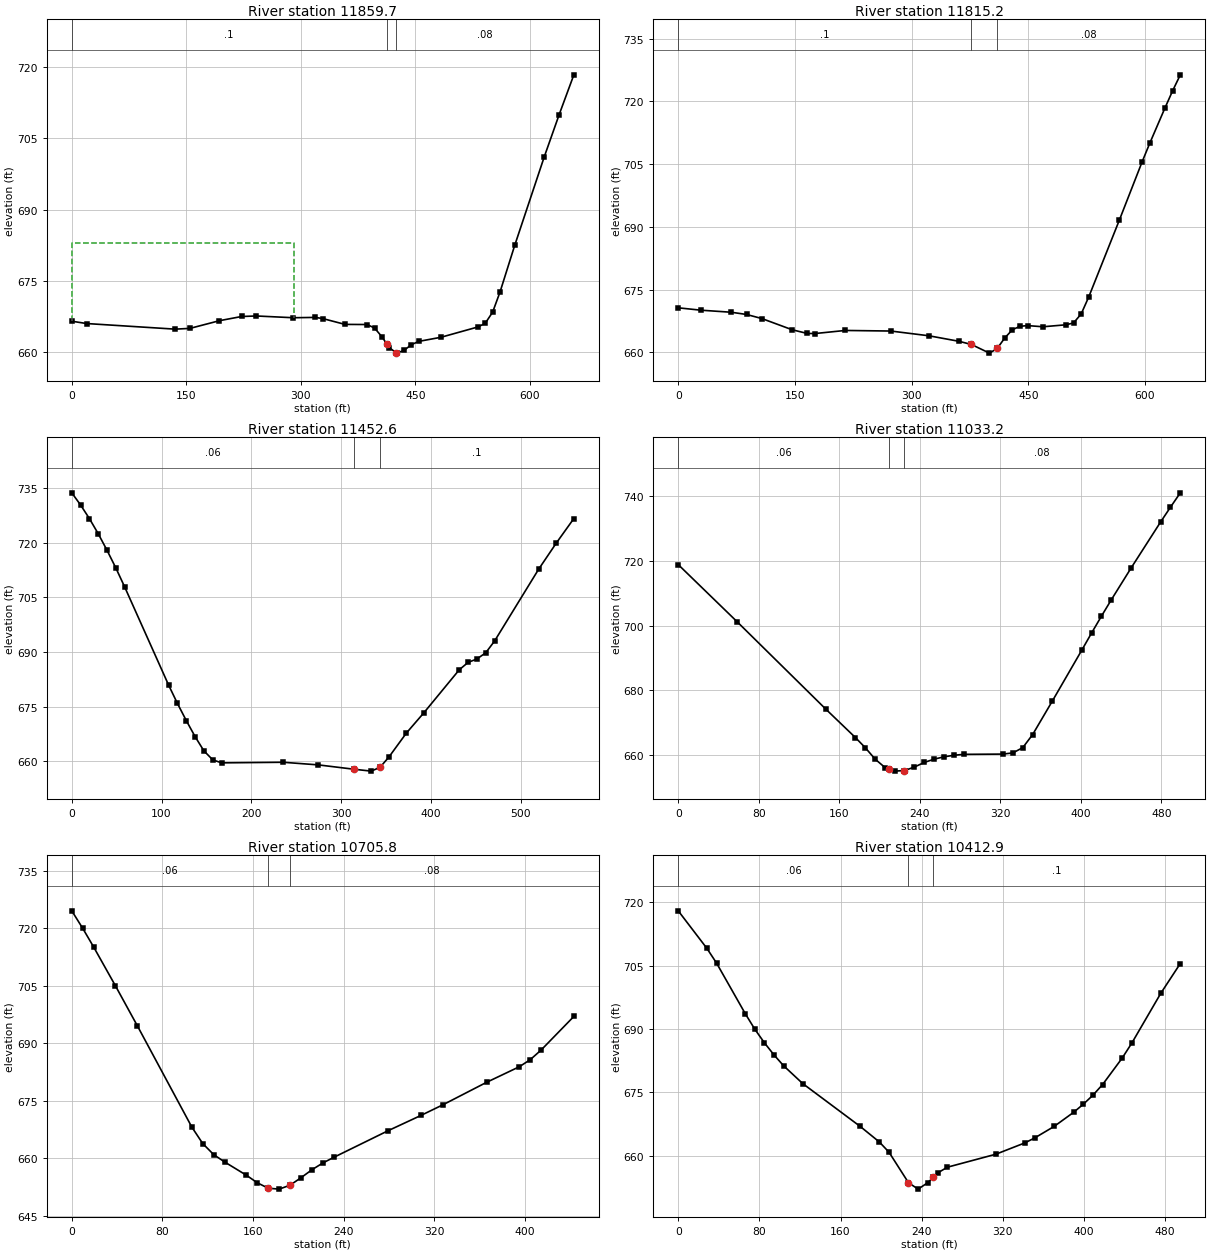
Type RM Length L Ch R = 1 ,11859.7 ,48.6,44.5,43.6
XS GIS Cut Line= 3
     1682787.521      479267.456     1683191.959      479229.019
     1683442.341      479251.919
#Sta/Elev= 30
       0  666.57    19.4  666.08   135.4   664.9   154.8  665.06   193.5  666.68
   222.5  667.56   241.8  667.67   290.2   667.3   319.2  667.37   328.9  667.12
   357.9   665.9   386.9  665.87   396.6  665.14   406.3   663.3   412.3 661.869
   415.9  661.01   425.3 659.896   425.6  659.86   435.3  660.44   444.9  661.64
   454.6  662.33   483.6  663.19     532  665.36   541.6  666.13   551.3  668.47
     561  672.71   580.3  682.54     619  701.15   638.4  709.97   657.7  718.36
#Mann= 3 , 0 , 0
       0      .1       0   412.3    .045       0   425.3     .08       0
#XS Ineff= 2 , 0
          291.07  682.98
Permanent Ineff=
       F       F
Bank Sta=412.3,425.3
XS Rating Curve= 0 ,0
Exp/Cntr=0.3,0.1

Type RM Length L Ch R = 1 ,11815.2 ,359.8,362.6,360.9
XS GIS Cut Line= 3
     1682802.212      479310.181     1683200.557      479272.322
     1683444.844      479294.665
#Sta/Elev= 30
       0  670.65    29.3  670.08    68.3  669.59    87.8  669.06   107.4  668.09
   146.4  665.41   165.9  664.52   175.7   664.5   214.7  665.24   273.3   665.1
   322.1  663.97   361.1  662.64   376.9 661.885   400.1  659.82     410  660.93
   419.8  663.46   429.6  665.42   439.4  666.24   449.2   666.4   468.8  666.12
   498.3  666.59   508.1  667.03   517.9  669.16   527.7  673.25     567   691.6
   596.4  705.59   606.2  710.02   625.8  718.48   635.6  722.56   645.4  726.34
#Mann= 3 , 0 , 0
       0      .1       0   376.9    .045       0     410     .08       0
Bank Sta=376.9,410
XS Rating Curve= 0 ,0
Exp/Cntr=0.3,0.1

Type RM Length L Ch R = 1 ,11452.6 ,405.6,419.4,432.4
XS GIS Cut Line= 2
     1682812.281      479625.703     1683371.544      479624.553
#Sta/Elev= 30
       0  733.69     9.8  730.36    19.6  726.64    29.4   722.5    39.2  717.96
    49.1  713.08    58.9  707.89   107.9  680.94   117.7  675.92   127.6   671.2
   137.4  666.81   147.2  662.91     157  660.46   166.8  659.62   235.5  659.78
   274.7  659.06     314  657.88   333.6  657.35   343.4   658.4   353.2  661.19
   372.8  667.81   392.5  673.43   431.7  685.16   441.5  687.18   451.3  688.11
   461.2  689.83     471  693.04     520   712.7   539.6  719.86   559.3  726.64
#Mann= 3 , 0 , 0
       0     .06       0     314    .045       0   343.4      .1       0
Bank Sta=314,343.4
XS Rating Curve= 0 ,0
Exp/Cntr=0.3,0.1

Type RM Length L Ch R = 1 ,11033.2 ,329.1,327.4,325
XS GIS Cut Line= 2
     1682835.571      479884.065     1683250.192      480161.262
#Sta/Elev= 30
       0  718.82    58.7  701.12   146.7  674.17     176  665.43   185.8   662.3
   195.6  658.77   205.4  656.17   209.2  655.74   215.2  655.06   224.2  655.24
   224.9  655.25   234.7  656.33   244.5  657.75   254.3  658.76     264  659.48
   273.8  659.95   283.6  660.24   322.7  660.32   332.5  660.69   342.3  662.32
   352.1  666.35   371.6  676.66     401  692.45   410.7  697.73   420.5  702.93
   430.3  707.99   449.8  717.72   479.2  731.97     489  736.54   498.8  740.98
#Mann= 3 , 0 , 0
       0     .06       0   209.2    .045       0   224.2     .08       0
Bank Sta=209.2,224.2
XS Rating Curve= 0 ,0
Exp/Cntr=0.3,0.1

Type RM Length L Ch R = 1 ,10705.8 ,303.5,292.9,282.3
XS GIS Cut Line= 2
     1682718.471      480190.727     1683111.785      480395.042
#Sta/Elev= 26
       0  724.49     9.6  719.96    19.3  715.07    38.5  704.97    57.8  694.57
     106  668.11   115.6  663.83   125.3  660.94   134.9  659.04   154.2  655.56
   163.8   653.6   173.4  652.19   183.1  651.95   192.7  652.98   202.3  654.91
     212     657   221.6  658.76   231.2  660.22   279.4   667.2   308.3  671.17
   327.6  673.93   366.1  679.78     395  683.84   404.7  685.69   414.3   688.2
   443.2  696.96
#Mann= 3 , 0 , 0
       0     .06       0   173.4    .045       0   192.7     .08       0
Bank Sta=173.4,192.7
XS Rating Curve= 0 ,0
Exp/Cntr=0.3,0.1

Type RM Length L Ch R = 1 ,10412.9 ,266.1,276.2,286.4
XS GIS Cut Line= 3
     1682631.031      480421.955     1682785.335      480546.409
     1683081.965      480554.848
#Sta/Elev= 30
       0  717.97    28.3  709.07    37.8  705.59    66.1  693.62    75.5  689.95
      85  686.72    94.4  683.87   103.8  681.32   122.7  677.09   179.4  666.94
   198.2  663.28   207.8  660.84     227  653.62   236.5   652.1   246.1  653.64
   251.5  654.92   255.7  655.91   265.2  657.28   313.1  660.36   341.8  663.05
   351.4  664.21   370.6  666.94   389.7  670.26   399.3  672.18   408.8  674.32
   418.4  676.86   437.6  683.09   447.1  686.63   475.8  698.47     495   705.5
#Mann= 3 , 0 , 0
       0     .06       0     227    .045       0   251.5      .1       0
Bank Sta=227,251.5
XS Rating Curve= 0 ,0
Exp/Cntr=0.3,0.1

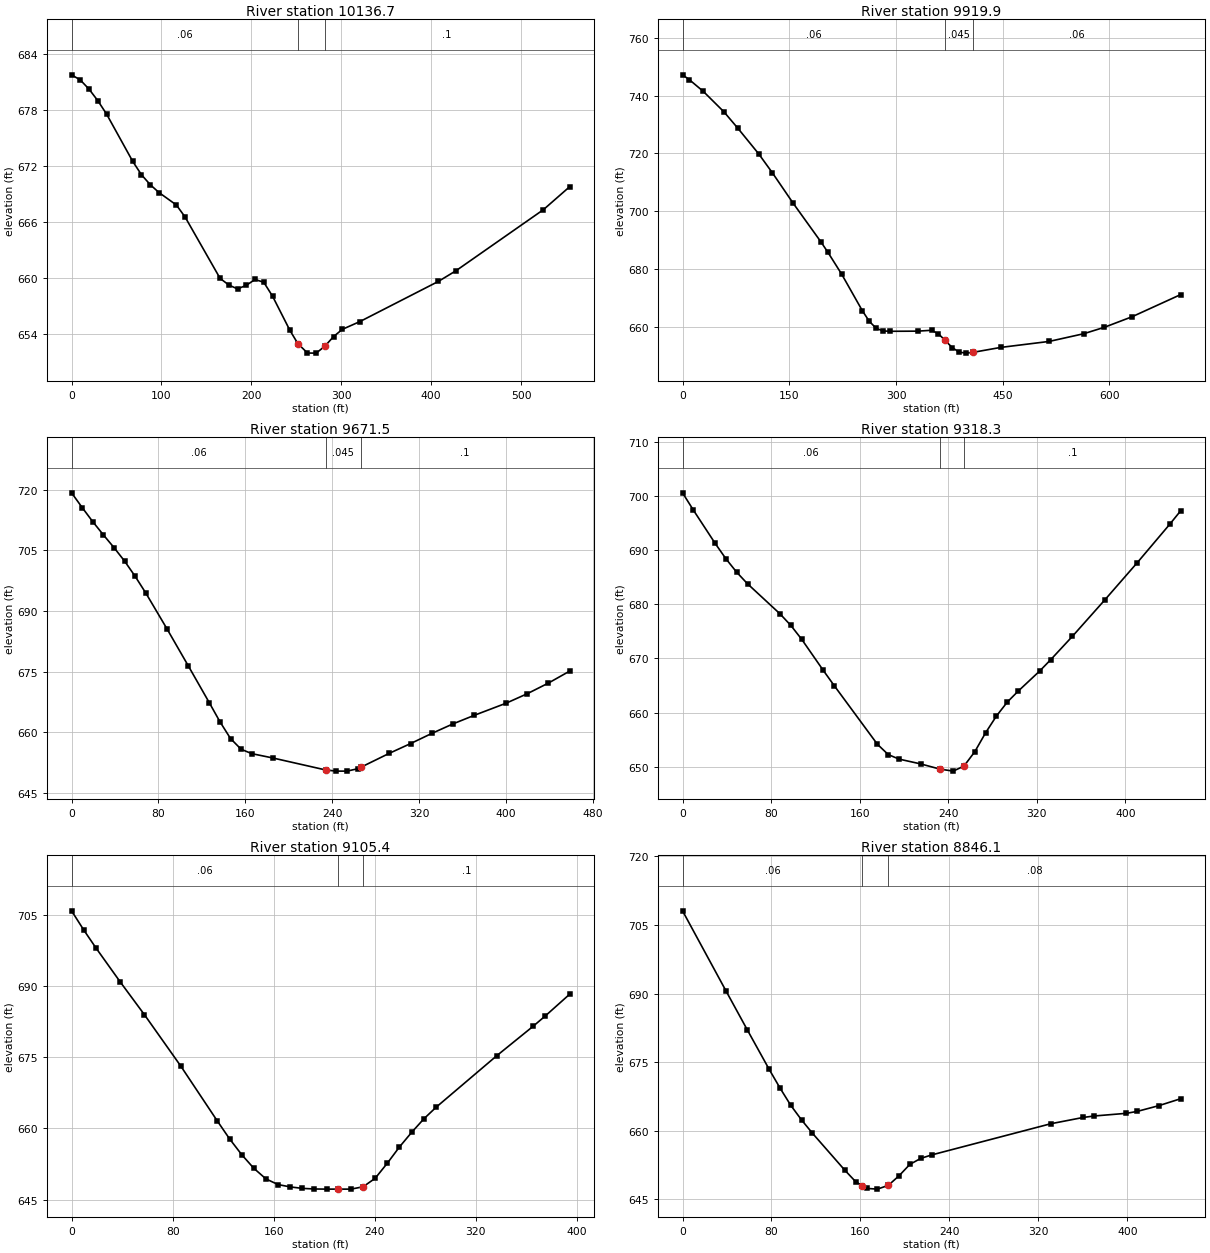
Type RM Length L Ch R = 1 ,10136.7 ,217.8,216.8,216.2
XS GIS Cut Line= 2
      1682535.18      480678.986     1683033.025       480921.81
#Sta/Elev= 30
       0  681.73     9.7  681.18    19.4   680.2    29.2  678.96    38.9  677.53
      68  672.46    77.7  671.03    87.5  669.96    97.2  669.12   116.6  667.78
   126.3  666.49   165.2  659.92   174.9  659.21   184.6  658.79   194.4  659.18
   204.1   659.8   213.8   659.5   223.5  658.02   242.9  654.34   251.7  652.93
   262.4  651.92   272.1  651.91   281.8  652.66   291.5  653.69   301.2  654.46
   320.7  655.29   408.1   659.6   427.6  660.74   524.8  667.28   553.9  669.73
#Mann= 3 , 0 , 0
       0     .06       0   251.7    .045       0   281.8      .1       0
Bank Sta=251.7,281.8
XS Rating Curve= 0 ,0
Exp/Cntr=0.3,0.1

Type RM Length L Ch R = 1 ,9919.9  ,254.3,248.5,242.4
XS GIS Cut Line= 2
      1682311.17      480826.916     1682954.664      481102.022
#Sta/Elev= 30
       0  747.16     9.7  745.45    29.2  741.44    58.3  734.35    77.8   728.7
   106.9  719.91   126.4  713.28   155.5  702.81   194.4  689.51   204.1  685.95
   223.6  678.34   252.7   665.7   262.4  662.06   272.2  659.62   281.9  658.72
   291.6   658.6   330.5  658.65   349.9  658.95   359.6  657.72   368.5  655.59
   379.1  652.94   388.8   651.4   398.5  651.06   408.2  651.33   447.1  653.03
   515.2   655.1   563.8  657.76   592.9  659.99   631.8  663.63   699.8  671.25
#Mann= 3 , 0 , 0
       0     .06       0   368.5    .045       0   408.2     .06       0
Bank Sta=368.5,408.2
XS Rating Curve= 0 ,0
Exp/Cntr=0.3,0.1

Type RM Length L Ch R = 1 ,9671.5  ,346.6,353.1,359.1
XS GIS Cut Line= 2
     1682388.744      481181.178     1682841.268      481253.704
#Sta/Elev= 30
       0  719.26     9.8   715.6    19.5  712.12    29.2  708.88      39  705.72
    48.8  702.36    58.5   698.6    68.3  694.47    87.8   685.6   107.3  676.49
   126.8  667.29   136.5  662.63   146.3  658.44     156   655.8   165.8  654.71
   185.3  653.63     234  650.66   243.8  650.38   253.5  650.38   263.3  650.97
   266.1  651.32   292.5   654.8     312   657.2   331.5  659.71     351  662.07
   370.5  664.18   399.8  667.18   419.3  669.53   438.8  672.17   458.3  675.12
#Mann= 3 , 0 , 0
       0     .06       0     234    .045       0   266.1      .1       0
Bank Sta=234,266.1
XS Rating Curve= 0 ,0
Exp/Cntr=0.3,0.1

Type RM Length L Ch R = 1 ,9318.3  ,213.2,213,213
XS GIS Cut Line= 2
     1682318.028      481445.934     1682732.342      481620.818
#Sta/Elev= 30
       0  700.57     9.8  697.38    29.3  691.29    39.1  688.42    48.9  685.92
    58.7  683.78      88  678.24    97.8   676.1   107.5  673.57   127.1   667.8
   136.9  665.01     176  654.16   185.8  652.26   195.5  651.43   215.1  650.54
   232.3  649.59   244.4  649.21   254.2  650.15     264  652.82   273.7  656.29
   283.5  659.39   293.3  661.96   303.1  663.97   322.6   667.7   332.4  669.76
     352  674.07   381.3   680.8   410.6  687.67   439.9  694.75   449.7  697.22
#Mann= 3 , 0 , 0
       0     .06       0   232.3    .045       0   254.2      .1       0
Bank Sta=232.3,254.2
XS Rating Curve= 0 ,0
Exp/Cntr=0.3,0.1

Type RM Length L Ch R = 1 ,9105.4  ,251.7,259.2,266.5
XS GIS Cut Line= 2
     1682291.494      481661.996     1682654.994      481814.287
#Sta/Elev= 29
       0  705.84     9.6  701.82    19.2  698.06    38.4   690.9    57.7  683.94
    86.5   673.1   115.4  661.54     125  657.81   134.6  654.48   144.2   651.6
   153.8  649.36   163.4  648.16     173  647.67   182.6  647.36   192.2  647.23
   201.9   647.2   210.5   647.2   221.1   647.2   230.7  647.69   240.3  649.49
   249.9  652.67   259.5  656.09   269.2  659.18   278.8  662.01   288.4  664.43
   336.4  675.29   365.3  681.52   374.9  683.69   394.1  688.25
#Mann= 3 , 0 , 0
       0     .06       0   210.5    .045       0   230.7      .1       0
Bank Sta=210.5,230.7
XS Rating Curve= 0 ,0
Exp/Cntr=0.3,0.1

Type RM Length L Ch R = 1 ,8846.1  ,366.8,364.3,361.4
XS GIS Cut Line= 2
     1682181.604      481795.146     1682516.942      482091.979
#Sta/Elev= 25
       0  708.09    38.9  690.66    58.4  681.99    77.9  673.43    87.6  669.36
    97.4  665.53   107.1  662.34   116.8  659.46     146  651.35   155.8  648.83
   161.7  647.95   165.5  647.39   175.2  647.23     185  648.05   194.7  650.15
   204.4  652.64   214.2  653.95   223.9   654.7     331  661.52   360.2   662.9
     370  663.22   399.2  663.81   408.9  664.23   428.4  665.49   447.8  666.99
#Mann= 3 , 0 , 0
       0     .06       0   161.7    .045       0     185     .08       0
Bank Sta=161.7,185
XS Rating Curve= 0 ,0
Exp/Cntr=0.3,0.1

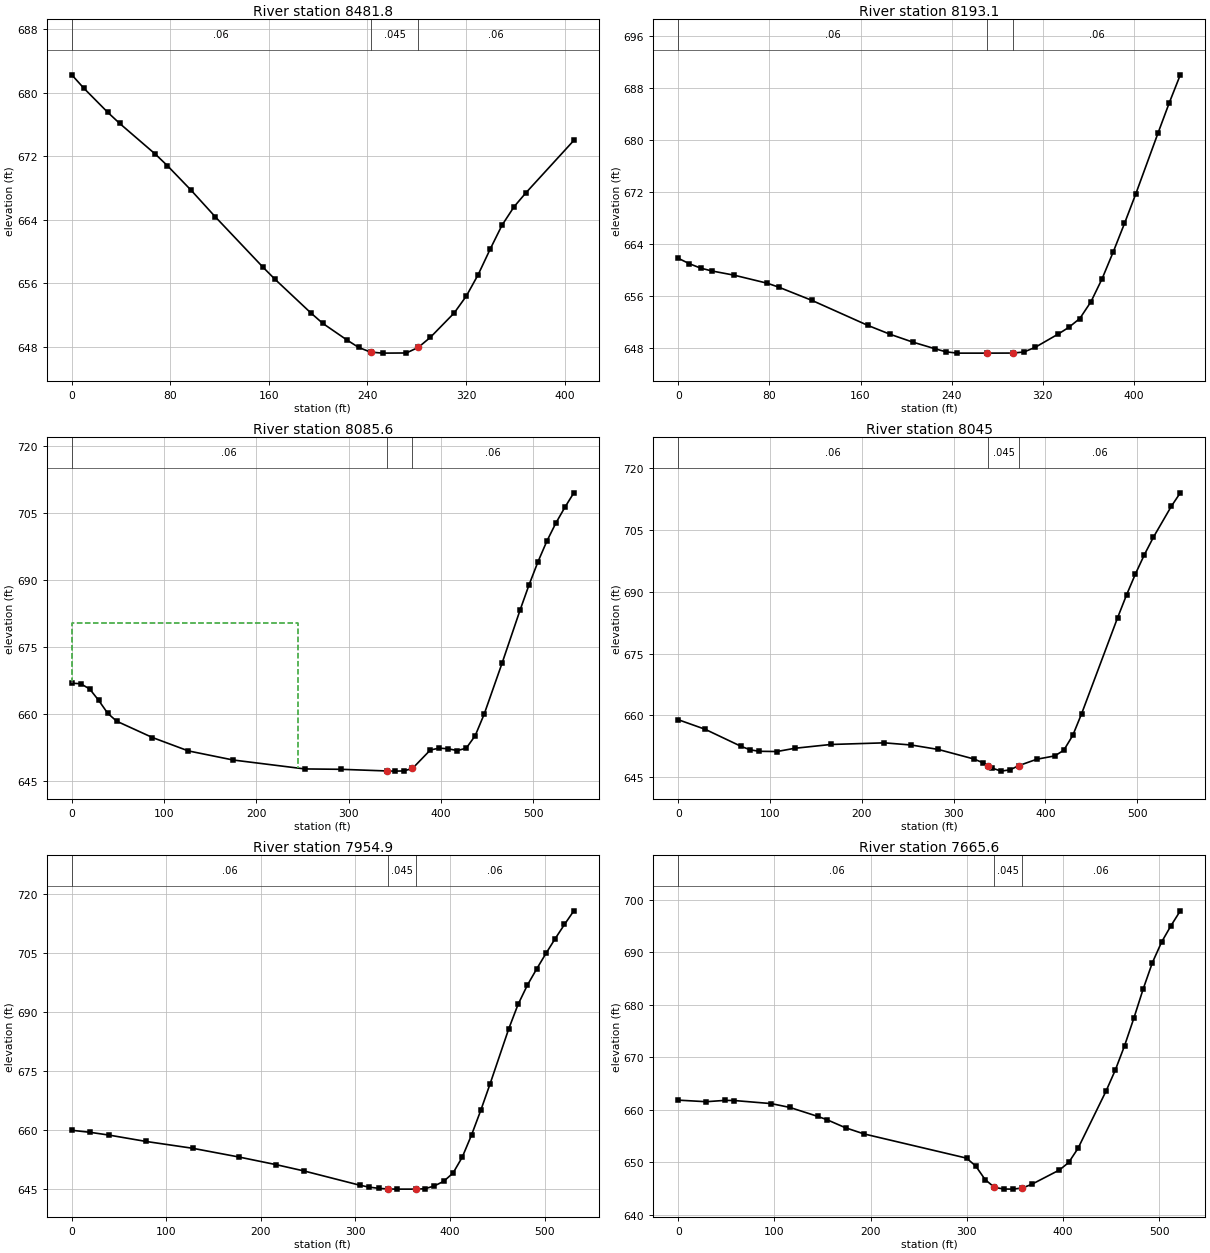
Type RM Length L Ch R = 1 ,8481.8  ,287.3,288.7,290.1
XS GIS Cut Line= 2
     1681958.754      482091.676     1682295.713      482320.768
#Sta/Elev= 27
       0  682.25     9.7  680.58    29.1  677.54    38.8  676.14    67.9  672.25
    77.6  670.81      97  667.69   116.4  664.38   155.2  658.02   164.9  656.51
     194  652.27   203.7  650.95   223.1  648.88   232.8  647.92   242.5  647.33
   252.2   647.2   271.6  647.22   281.3  647.93     291  649.18   310.4  652.26
   320.2  654.38   329.8  657.07   339.6   660.3   349.2  663.31     359  665.64
   368.7  667.41   407.5  673.99
#Mann= 3 , 0 , 0
       0     .06       0   242.5    .045       0   281.3     .06       0
Bank Sta=242.5,281.3
XS Rating Curve= 0 ,0
Exp/Cntr=0.3,0.1

Type RM Length L Ch R = 1 ,8193.1  ,114.2,107.5,100.9
XS GIS Cut Line= 2
     1681751.588      482249.291     1682093.633      482526.933
#Sta/Elev= 29
       0  661.81     9.8  660.97    19.6   660.3    29.4  659.86      49  659.21
    78.3  657.96    88.1  657.37   117.5  655.31   166.4  651.47     186   650.1
   205.6  648.91   225.2  647.88     235   647.4   244.8   647.2   271.2   647.2
   293.7  647.21   303.5  647.38   313.3   648.1   332.9  650.08   342.6  651.15
   352.4  652.53   362.2  655.12     372  658.67   381.8  662.82   391.6  667.17
   401.4  671.67     421  681.08   430.8  685.71   440.6  690.07
#Mann= 3 , 0 , 0
       0     .06       0   271.2    .045       0   293.7     .06       0
Bank Sta=271.2,293.7
XS Rating Curve= 0 ,0
Exp/Cntr=0.3,0.1

Type RM Length L Ch R = 1 ,8085.6  ,40.9,40.6,40.9
XS GIS Cut Line= 2
     1681586.572       482382.78     1682093.632      482580.021
#Sta/Elev= 30
       0  666.89     9.7  666.76    19.4  665.59    29.2  663.03    38.9  660.16
    48.6  658.38    87.4  654.72   126.3  651.72   174.9  649.68   252.6  647.68
   291.5   647.6   341.1  647.23   349.8  647.19   359.5  647.23   369.2  647.78
   388.6  651.93   398.3  652.34     408  652.19   417.8  651.79   427.5  652.33
   437.2  655.13   446.9  659.94   466.4  671.42   485.8  683.25   495.5  688.89
   505.2  694.07   514.9  698.73   524.6  702.75   534.4  706.29   544.1  709.53
#Mann= 3 , 0 , 0
       0     .06       0   341.1    .045       0   369.2     .06       0
#XS Ineff= 2 , 0
          245.17  680.31
Permanent Ineff=
       F       F
Bank Sta=341.1,369.2
XS Rating Curve= 0 ,0
Exp/Cntr=0.3,0.1

Type RM Length L Ch R = 1 ,8045    ,92.8,90.1,86.9
XS GIS Cut Line= 2
      1681583.75      482424.156      1682093.63      482622.495
#Sta/Elev= 30
       0  658.97    29.3  656.65    68.4  652.52    78.2  651.68    87.9  651.31
   107.5  651.25     127  652.04   166.1  652.96   224.7  653.36     254  652.83
   283.3  651.76   322.4  649.43   332.2  648.51   337.8  647.78   341.9  647.25
   351.7   646.5   361.5  646.81   371.2  647.84   390.8  649.39   410.3  650.19
   420.1  651.56   429.9  655.16   439.6  660.45   478.7  683.67   488.5  689.22
   498.2  694.32     508  699.01   517.8  703.23   537.3  710.72   547.1  713.99
#Mann= 3 , 0 , 0
       0     .06       0   337.8    .045       0   371.2     .06       0
#XS Ineff= 2 , 0
          226.08  652.98
Permanent Ineff=
       F       F
Bank Sta=337.8,371.2
XS Rating Curve= 0 ,0
Exp/Cntr=0.3,0.1

Type RM Length L Ch R = 1 ,7954.9  ,294.6,289.3,283.6
XS GIS Cut Line= 2
     1681574.073      482566.007     1682093.628      482675.063
#Sta/Elev= 30
       0  659.94    19.7  659.41    39.3  658.72    78.6   657.1   127.8  655.37
     177  653.14   216.3   651.2   245.8   649.6   304.8  645.98   314.6   645.5
   324.4  645.21   334.3  645.04   344.1     645   363.8     645   373.6   645.1
   383.4  645.82   393.2  646.97   403.1  649.06   412.9  653.11   422.7  658.73
   432.6  665.08   442.4  671.77   462.1  685.72   471.9  691.87   481.7  696.75
   491.6  700.89   501.4  704.82   511.2  708.59     521  712.18   530.9  715.64
#Mann= 3 , 0 , 0
       0     .06       0   334.3    .045       0   363.8     .06       0
Bank Sta=334.3,363.8
XS Rating Curve= 0 ,0
Exp/Cntr=0.3,0.1

Type RM Length L Ch R = 1 ,7665.6  ,68.2,68.2,68.3
XS GIS Cut Line= 2
     1681579.667      482919.787      1682101.47      482922.275
#Sta/Elev= 30
       0  661.86      29  661.56    48.3  661.81      58  661.79    96.6   661.2
     116  660.47     145  658.76   154.6  658.13   173.9  656.59   193.3  655.41
   299.6  650.81   309.2   649.3   318.9  646.73   328.6  645.24   338.2  644.92
   347.9   644.9   357.5  645.11   367.2   645.8   396.2  648.55   405.8  649.98
   415.5  652.68   444.5  663.54   454.2  667.57   463.8   672.2   473.5  677.47
   483.2  683.04   492.8  688.08   502.5  692.04   512.2  695.14   521.8  697.94
#Mann= 3 , 0 , 0
       0     .06       0   328.6    .045       0   357.5     .06       0
Bank Sta=328.6,357.5
XS Rating Curve= 0 ,0
Exp/Cntr=0.3,0.1