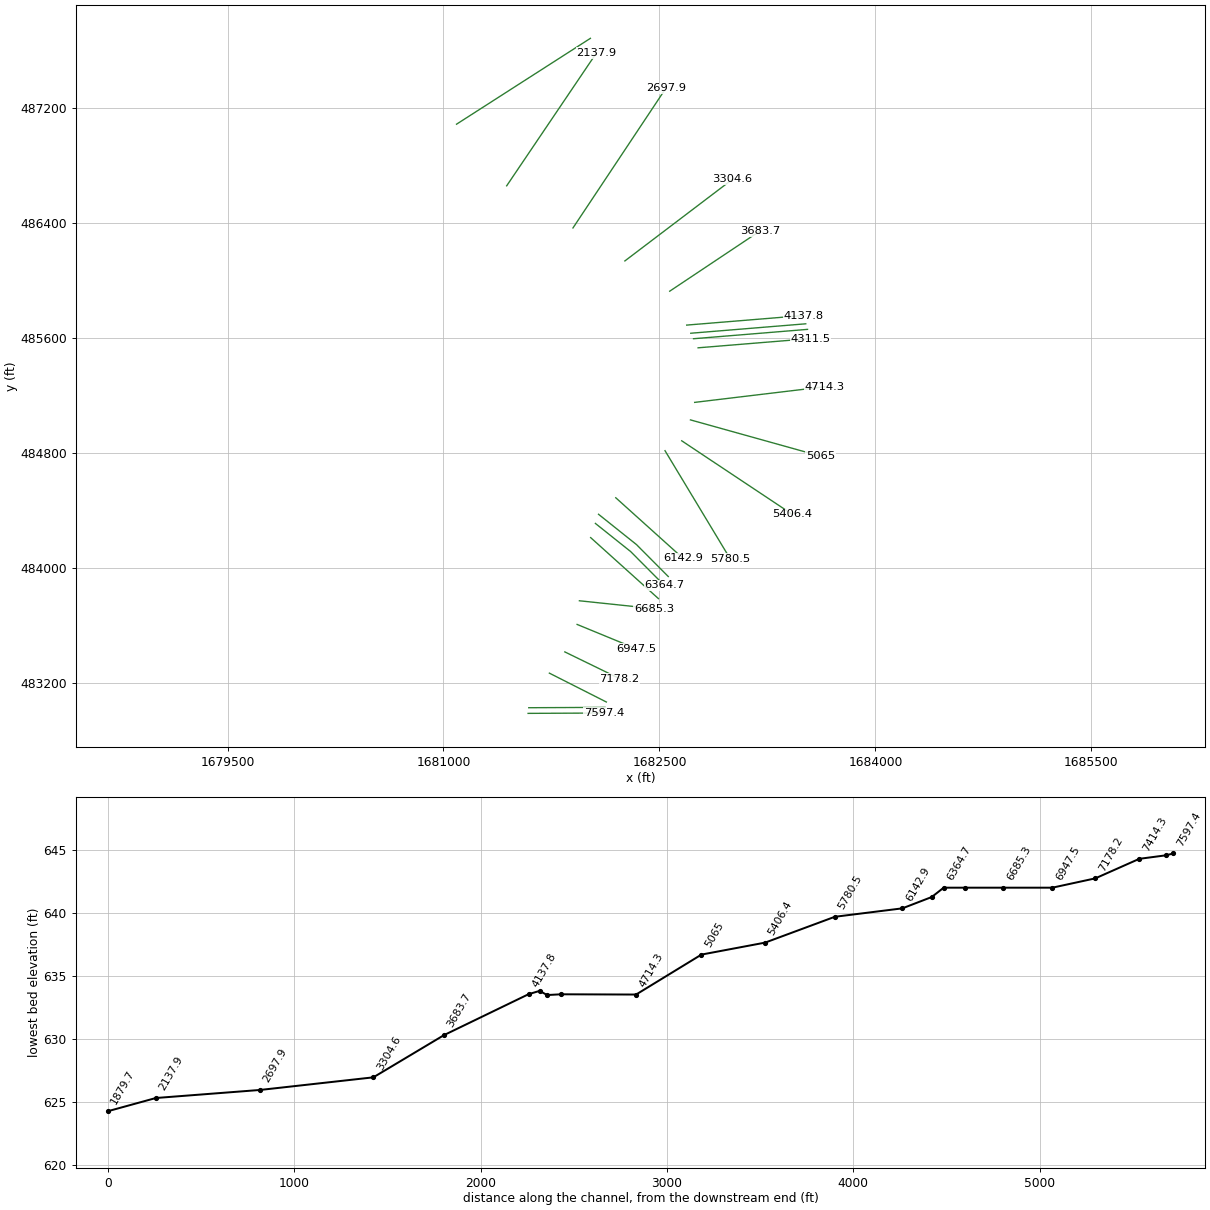
HEC-RAS study ClymerCk.prj: ClymerCk

--- ClymerCk.g01 (geometry) --- (continued)

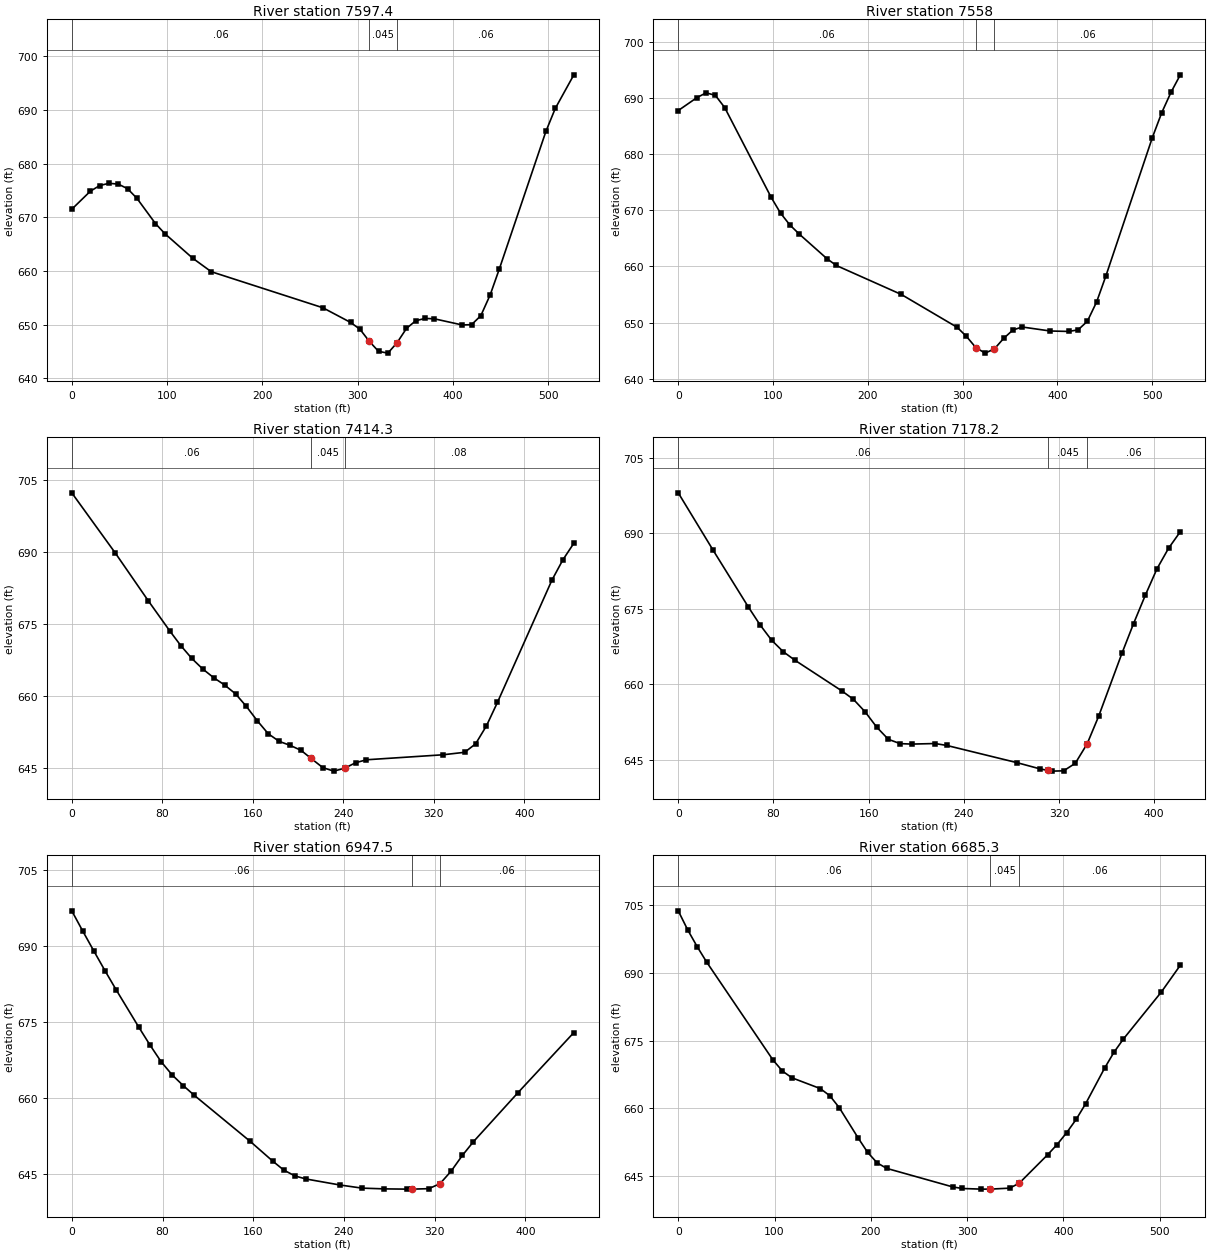
Type RM Length L Ch R = 1 ,7597.4  ,39.3,39.3,39.3
XS GIS Cut Line= 2
     1681587.764      482987.284     1682114.537      482989.795
#Sta/Elev= 30
       0   671.5    19.5  674.86    29.3  675.91      39  676.33    48.8  676.18
    58.5  675.33    68.3  673.55    87.8  668.84    97.6  666.97   126.8   662.4
   146.3  659.88   263.4  653.17   292.6  650.43   302.4  649.16   312.2  646.91
   321.9  645.05   331.7  644.72   341.4  646.68   351.2  649.32   360.9  650.75
   370.7  651.18   380.4  651.11   409.7  649.96   419.5  650.02   429.2  651.69
     439  655.56   448.7  660.43   497.5     686   507.3  690.26   526.8  696.52
#Mann= 3 , 0 , 0
       0     .06       0   312.2    .045       0   341.4     .06       0
Bank Sta=312.2,341.4
XS Rating Curve= 0 ,0
Exp/Cntr=0.3,0.1

Type RM Length L Ch R = 1 ,7558    ,154.5,143.8,133
XS GIS Cut Line= 2
     1681592.486      483026.642     1682122.156      483029.167
#Sta/Elev= 30
       0  687.75    19.6  690.04    29.4  690.91    39.2  690.45      49  688.29
    98.1  672.28   107.9   669.5   117.7   667.4   127.5  665.79   156.9  661.38
   166.8  660.17   235.4  655.01   294.3  649.16   304.1  647.54   313.9  645.57
   323.7  644.57   333.5  645.31   343.3  647.19   353.1  648.69   362.9  649.22
   392.4  648.51     412  648.43   421.8  648.71   431.6  650.23   441.4  653.68
   451.2  658.32   500.2  682.94   510.1  687.37   519.9  691.01   529.7  694.11
#Mann= 3 , 0 , 0
       0     .06       0   313.9    .045       0   333.5     .06       0
Bank Sta=313.9,333.5
XS Rating Curve= 0 ,0
Exp/Cntr=0.3,0.1

Type RM Length L Ch R = 1 ,7414.3  ,235.5,236.1,236.5
XS GIS Cut Line= 2
     1681735.668      483267.301     1682131.296      483066.467
#Sta/Elev= 30
       0  702.39    38.6  689.78    67.5  679.89    86.8   673.5    96.4  670.48
   106.1  667.81   115.7  665.62   125.4   663.8     135  662.28   144.7  660.43
   154.3   657.8     164  654.79   173.6   652.1   183.3   650.5   192.9  649.68
   202.6  648.63   211.3  646.98   221.8  645.03   231.5  644.29   241.1  644.89
   250.8  646.04   260.4  646.66   327.9   647.7   347.2  648.22   356.9  649.99
   366.5  653.76   376.2  658.65   424.4   684.2     434   688.4   443.7  691.87
#Mann= 3 , 0 , 0
       0     .06       0   211.3    .045       0   241.1     .08       0
Bank Sta=211.3,241.1
XS Rating Curve= 0 ,0
Exp/Cntr=0.3,0.1

Type RM Length L Ch R = 1 ,7178.2  ,229.2,230.7,232
XS GIS Cut Line= 2
     1681842.922      483415.148     1682222.099      483229.924
#Sta/Elev= 30
       0  698.01    29.4  686.58    58.9  675.35    68.7  671.81    78.5  668.74
    88.3  666.45    98.1  664.76   137.4  658.69   147.2  657.01     157  654.54
   166.8  651.48   176.6  649.06   186.5   648.2   196.3  648.11   215.9  648.22
   225.7  647.84   284.6  644.43   304.2  643.18     311  642.87     314  642.74
   323.9   642.8   333.7  644.29   343.7648.1633   353.3   653.6   372.9  666.12
   382.7  672.04   392.6  677.68   402.4  682.93   412.2  687.03     422  690.29
#Mann= 3 , 0 , 0
       0     .06       0     311    .045       0   343.7     .06       0
Bank Sta=311,343.7
XS Rating Curve= 0 ,0
Exp/Cntr=0.3,0.1

Type RM Length L Ch R = 1 ,6947.5  ,255.3,262.2,268.5
XS GIS Cut Line= 2
     1681928.175      483606.369     1682337.506      483437.675
#Sta/Elev= 28
       0  696.98     9.8  692.93    19.7  688.95    29.5  685.07    39.4  681.28
      59  674.03    68.9  670.49    78.7   667.2    88.6  664.54    98.4  662.43
   108.2   660.5   157.4  651.42   177.1  647.55   186.9  645.77   196.8   644.6
   206.6     644   236.1  642.83   255.8   642.2   275.5  642.05   295.2     642
   300.4     642   314.8  642.09   324.7  643.08   334.5  645.55   344.4  648.66
   354.2  651.38   393.5  661.07   442.7  672.93
#Mann= 3 , 0 , 0
       0     .06       0   300.4    .045       0   324.7     .06       0
Bank Sta=300.4,324.7
XS Rating Curve= 0 ,0
Exp/Cntr=0.3,0.1

Type RM Length L Ch R = 1 ,6685.3  ,221.2,206,191
XS GIS Cut Line= 2
     1681944.102      483771.007     1682462.495      483716.459
#Sta/Elev= 30
       0  703.81     9.8  699.59    19.7  695.84    29.5  692.43    98.4  670.67
   108.2  668.22     118  666.73   147.5  664.33   157.4  662.74   167.2  660.09
   186.9  653.33   196.7  650.15   206.5  647.84   216.4  646.61   285.2  642.48
     295  642.14   314.7     642   323.8     642   344.2  642.22   354.1  643.33
   383.6  649.65   393.4  651.91   403.2  654.51   413.1  657.47   422.9  660.93
   442.6  668.84   452.4  672.39   462.2  675.34   501.6  685.78   521.3  691.72
#Mann= 3 , 0 , 0
       0     .06       0   323.8    .045       0   354.1     .06       0
Bank Sta=323.8,354.1
XS Rating Curve= 0 ,0
Exp/Cntr=0.3,0.1

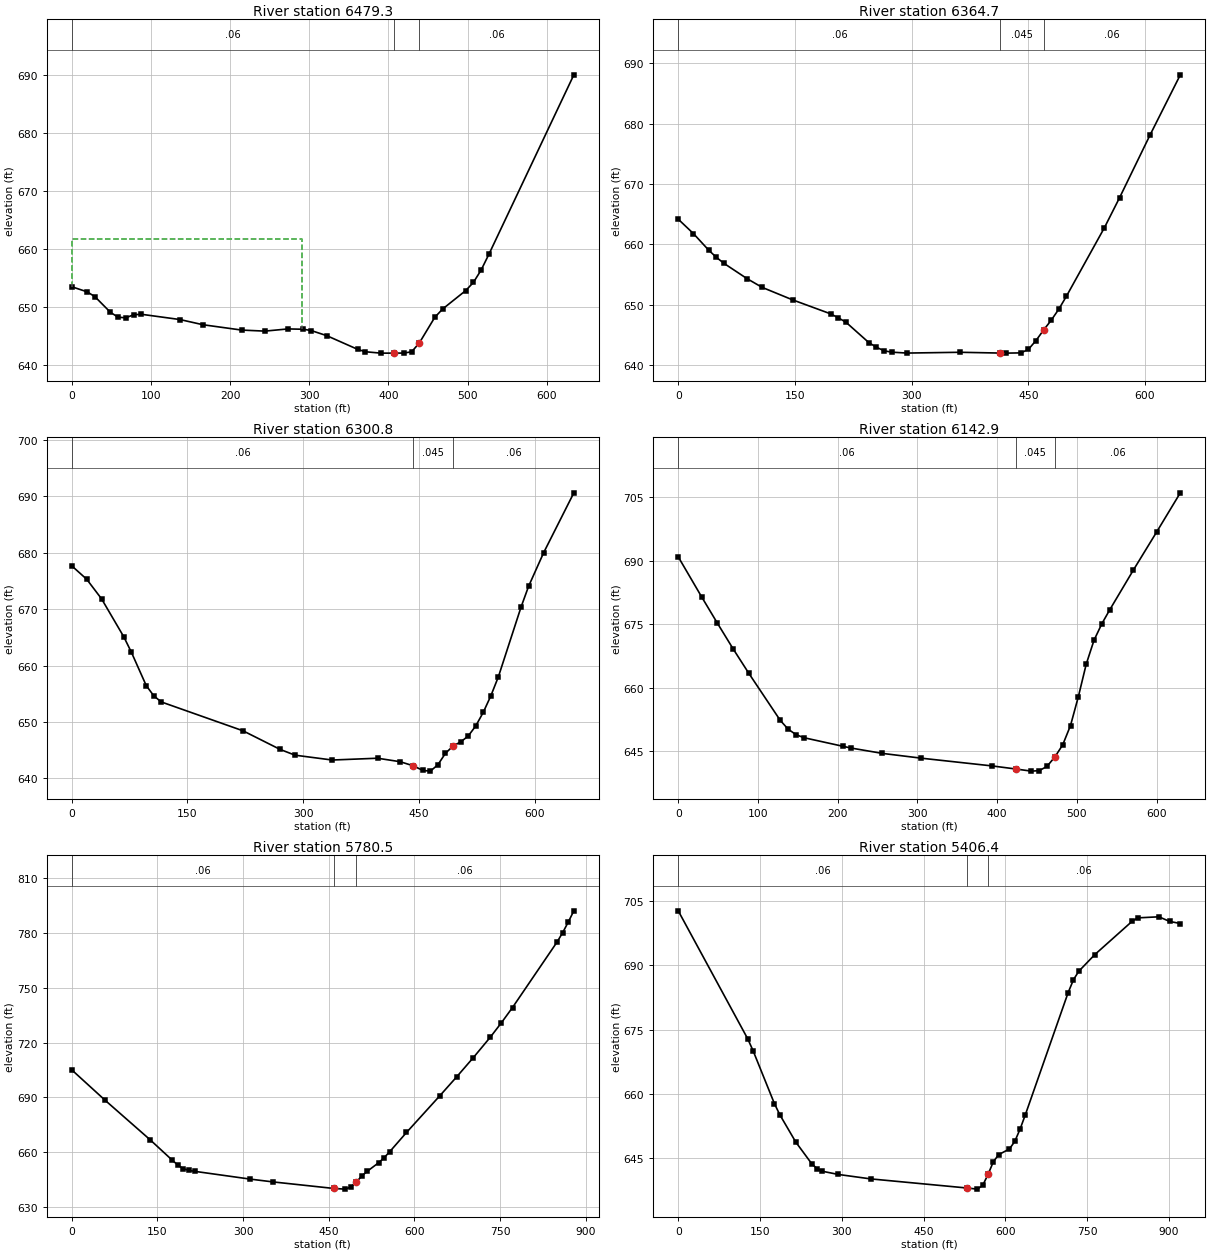
Type RM Length L Ch R = 1 ,6479.3  ,115.1,114.7,114.2
XS GIS Cut Line= 2
     1682022.358      484210.664     1682493.231      483785.906
#Sta/Elev= 30
       0  653.46    19.5  652.58    29.3  651.74    48.8  649.05    58.5   648.2
    68.3   648.1      78  648.62    87.8  648.71   136.6   647.8   165.8   646.9
   214.6  645.98   243.9   645.8   273.2  646.18   292.7  646.12   302.4   645.9
     322  645.02     361  642.66   370.7  642.24   390.2     642   407.3     642
   419.5  642.01   429.3  642.23     439  643.75   458.5  648.17   468.3   649.6
   497.6   652.8   507.3   654.2   517.1  656.35   526.8  659.04   634.2  690.05
#Mann= 3 , 0 , 0
       0     .06       0   407.3    .045       0     439     .06       0
#XS Ineff= 2 , 0
          291.07  661.68
Permanent Ineff=
       F       F
Bank Sta=407.3,439
XS Rating Curve= 0 ,0
Exp/Cntr=0.3,0.1

Type RM Length L Ch R = 1 ,6364.7  ,63.9,63.9,64
XS GIS Cut Line= 3
     1682055.253       484309.36     1682300.141      484113.463
     1682533.982       483877.98
#Sta/Elev= 30
       0  664.17    19.6  661.78    39.2  659.04      49  657.86    58.8  656.86
    88.2  654.35   107.8  652.89     147  650.82     196   648.5   205.8  647.84
   215.6  647.12     245  643.75   254.8  642.97   264.6  642.39   274.4  642.16
     294  642.01   362.4  642.14   414.2  642.01     421     642   440.5  642.04
   450.2  642.62     460  644.09   470.2 645.906   479.5  647.44   489.3  649.28
     499   651.4   547.9  662.76   567.4  667.73   606.4  678.06   645.5  688.07
#Mann= 3 , 0 , 0
       0     .06       0   414.2    .045       0   470.2     .06       0
Bank Sta=414.2,470.2
XS Rating Curve= 0 ,0
Exp/Cntr=0.3,0.1

Type RM Length L Ch R = 1 ,6300.8  ,156.4,157.8,158.7
XS GIS Cut Line= 3
     1682076.997      484372.984     1682340.635      484162.088
     1682561.352      483939.822
#Sta/Elev= 30
       0  677.69    19.3  675.32    38.6  671.84    67.5  665.08    77.2  662.38
    96.5  656.45   106.1  654.66   115.8  653.55   221.9  648.42   270.1  645.11
   289.4  644.09   337.6  643.23   396.4  643.55   425.7  642.93   442.6  642.21
   455.1  641.38   464.9  641.26   474.6   642.4   484.4  644.43   494.6645.7585
     504  646.43   513.8  647.48   523.6  649.27   533.4   651.7   543.2  654.62
     553  658.01   582.3  670.35   592.1  674.05   611.7  680.04   650.8  690.65
#Mann= 3 , 0 , 0
       0     .06       0   442.6    .045       0   494.6     .06       0
Bank Sta=442.6,494.6
XS Rating Curve= 0 ,0
Exp/Cntr=0.3,0.1

Type RM Length L Ch R = 1 ,6142.9  ,369.3,362.5,355.9
XS GIS Cut Line= 2
     1682196.909      484487.908     1682664.455      484066.178
#Sta/Elev= 29
       0  690.94    29.5  681.44    49.2  675.25    68.9   669.2    88.5  663.45
   127.9  652.35   137.7  650.29   147.6  648.98   157.4  648.26   206.6  646.22
   216.4  645.82   255.8  644.55     305  643.41   393.5  641.59     423  640.87
   442.7  640.36   452.6  640.47   462.4  641.47   472.4 643.738   482.1  646.55
   491.9  651.12   501.8  657.97   511.6   665.6   521.4  671.27   531.3  675.18
   541.1  678.44   570.6  687.78   600.1  696.86   629.6  706.05
#Mann= 3 , 0 , 0
       0     .06       0     423    .045       0   472.4     .06       0
Bank Sta=423,472.4
XS Rating Curve= 0 ,0
Exp/Cntr=0.3,0.1

Type RM Length L Ch R = 1 ,5780.5  ,362.3,374.1,384.3
XS GIS Cut Line= 2
     1682538.799      484815.576     1682991.863      484062.326
#Sta/Elev= 30
       0  705.07    58.6  688.34   136.7  666.88   175.8  655.59   185.6  652.92
   195.3  650.88   205.1  649.94   214.9  649.46   312.5  645.18   351.6  643.67
     459  640.05   478.6  639.69   488.3  640.79   498.3643.6192   507.9  646.94
   517.6  649.54   537.2  654.15   546.9  656.94   556.7  660.23     586  670.74
   644.6  690.96   673.9  701.26   703.2  711.85   732.5  722.89     752  730.82
   771.6  739.25   849.7   775.2   859.5  780.35   869.2   786.1     879  792.26
#Mann= 3 , 0 , 0
       0     .06       0     459    .045       0   498.3     .06       0
Bank Sta=459,498.3
XS Rating Curve= 0 ,0
Exp/Cntr=0.3,0.1

Type RM Length L Ch R = 1 ,5406.4  ,336.1,341.4,348.1
XS GIS Cut Line= 2
     1682654.891      484884.436     1683421.218       484373.59
#Sta/Elev= 30
       0  702.79   127.4  672.84   137.2  670.07   176.4  657.67   186.2  655.08
   215.6  648.66   244.9  643.58   254.7  642.43   264.5  641.82   293.9  641.07
   352.7  640.04   529.1  637.91   548.7  637.64   558.5  638.52   568.3  641.07
   578.1  644.07   587.9  645.72   607.5  647.04   617.3   648.8   627.1   651.7
   636.8  655.08   715.2  683.63     725  686.67   734.8  688.65   764.2  692.55
   832.8  700.36   842.6  701.14   881.8  701.39   901.4  700.31     921  699.82
#Mann= 3 , 0 , 0
       0     .06       0   529.1    .045       0   568.3     .06       0
Bank Sta=529.1,568.3
XS Rating Curve= 0 ,0
Exp/Cntr=0.3,0.1

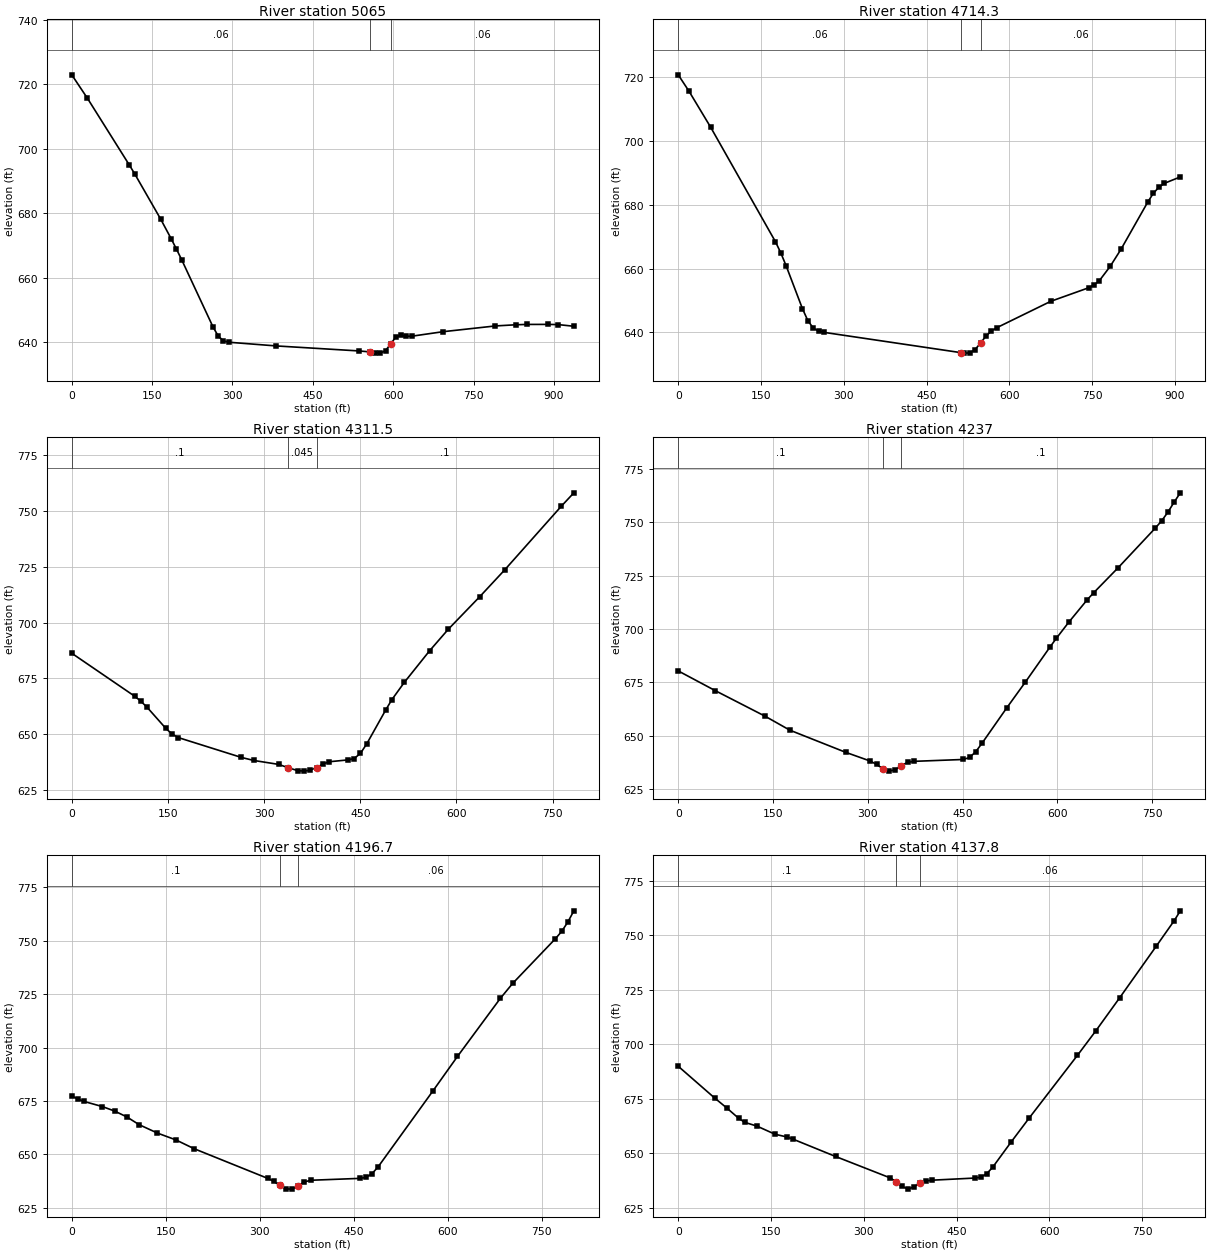
Type RM Length L Ch R = 1 ,5065    ,341.5,350.7,359.9
XS GIS Cut Line= 2
     1682715.458      485030.035     1683618.125      484777.749
#Sta/Elev= 30
       0  722.89    29.3  715.61   107.4  694.97   117.2   692.3     166  678.19
   185.5  672.14   195.3  668.95     205  665.68   263.6  644.83   273.4  641.97
   283.1   640.5   292.9  640.07   380.8  638.93     537  637.36   556.5  637.07
   566.3  636.81     576  636.69   585.8  637.46   595.6  639.61   605.3  641.74
   615.1  642.21   624.8  641.92   634.6  641.93   693.2  643.33   790.8  645.11
   829.9  645.48   849.4  645.58   888.4  645.59     908  645.53   937.3  645.01
#Mann= 3 , 0 , 0
       0     .06       0   556.5    .045       0   595.6     .06       0
Bank Sta=556.5,595.6
XS Rating Curve= 0 ,0
Exp/Cntr=0.3,0.1

Type RM Length L Ch R = 1 ,4714.3  ,406.7,402.7,398.5
XS GIS Cut Line= 2
     1682744.793      485151.903     1683647.726      485260.427
#Sta/Elev= 30
       0  720.61    19.6  715.45    58.7  704.22     176  668.41   185.8  664.88
   195.6  660.77   224.9  647.46   234.7  643.71   244.5  641.37   254.2  640.39
     264  640.02   511.3  633.69   518.3  633.52   528.1  633.58   537.8  634.65
   547.6  636.69   557.4  638.85   567.2  640.46     577  641.48   674.7  649.73
   743.2  653.96     753  654.81   762.8   656.2   782.3  660.65   801.9     666
   850.8   680.9   860.5  683.52   870.3  685.39   880.1  686.63   909.4  688.66
#Mann= 3 , 0 , 0
       0     .06       0   511.3    .045       0   547.6     .06       0
Bank Sta=511.3,547.6
XS Rating Curve= 0 ,0
Exp/Cntr=0.3,0.1

Type RM Length L Ch R = 1 ,4311.5  ,70.9,74.5,77.2
XS GIS Cut Line= 2
     1682768.468      485531.646     1683548.957      485595.815
#Sta/Elev= 30
       0  686.29    97.9   667.1   107.7  664.84   117.5   662.1   146.8  652.63
   156.6   650.1   166.4  648.53   264.3  639.69   283.9  638.31     323  636.54
   337.3  635.07   352.3  633.78   362.2  633.54     372  633.99   381.8  635.14
   391.6  636.68   401.4  637.73   430.7  638.56   440.5  639.18   450.3   641.5
   460.1  645.76   489.4  660.77   499.2  665.51   518.8   673.3     558  687.36
   587.3  697.04   636.3  711.59   675.4  723.64   763.5  752.07   783.1  758.08
#Mann= 3 , 0 , 0
       0      .1       0   337.3    .045       0   381.8      .1       0
Bank Sta=337.3,381.8
XS Rating Curve= 0 ,0
Exp/Cntr=0.3,0.1

Type RM Length L Ch R = 1 ,4237    ,40.5,40.3,40.9
XS GIS Cut Line= 2
     1682736.839      485594.899      1683528.63      485659.997
#Sta/Elev= 30
       0  680.41    58.8  671.14   137.3  659.22   176.6  652.66   264.8  642.31
     304  638.18   313.9  636.61   323.7  634.64   333.5  633.48   343.3  634.11
   353.1  636.11   362.9  637.58   372.7  638.06   451.2  638.94     461  639.88
   470.8  642.59   480.6  646.49   519.8  663.08   549.3  675.18   588.5  691.69
   598.3  695.66   617.9  703.19   647.3  713.77   657.2  716.95   696.4  728.82
   755.2  747.38     765  750.71   774.8  754.73   784.6  759.39   794.5  763.81
#Mann= 3 , 0 , 0
       0      .1       0   323.7    .045       0   353.1      .1       0
Bank Sta=323.7,353.1
XS Rating Curve= 0 ,0
Exp/Cntr=0.3,0.1

Type RM Length L Ch R = 1 ,4196.7  ,58.9,58.9,58.9
XS GIS Cut Line= 2
     1682717.723      485633.128     1683516.345      485698.788
#Sta/Elev= 30
       0  677.34     9.8   675.9    19.5   674.8    48.9  672.39    68.4  670.31
      88  667.54   107.5  663.94   136.8     660   166.1  656.83   195.4  652.69
   312.7  638.84   322.5  637.45   332.2  635.52     342  633.93   351.8  633.81
   361.6  635.44   371.3  637.16   381.1  637.95   459.3  638.83   469.1  639.26
   478.8  640.92   488.6  644.09   576.6   679.8   615.6  695.85     684  722.99
   703.6  729.95     772   750.9   781.8  754.25   791.5  758.55   801.3   763.9
#Mann= 3 , 0 , 0
       0      .1       0   332.2    .045       0   361.6     .06       0
Bank Sta=332.2,361.6
XS Rating Curve= 0 ,0
Exp/Cntr=0.3,0.1

Type RM Length L Ch R = 1 ,4137.8  ,442.3,454.1,465.4
XS GIS Cut Line= 2
     1682689.395      485689.779      1683498.14      485756.271
#Sta/Elev= 30
       0  689.96    58.7  675.42    78.2  670.87    97.8  666.04   107.5   664.2
   127.1   662.5   156.4  658.75     176  657.47   185.8  656.46   254.2  648.55
   342.2  638.75     352  637.02   361.6  634.81   371.5  633.55   381.3  634.66
   391.1  636.44   400.8  637.35   410.6  637.66   479.1  638.63   488.8  639.03
   498.6  640.61   508.4  643.66   537.7  655.05     567  666.11   645.3     695
   674.6  706.09   713.7  721.48   772.4     745   801.7  756.83   811.5  761.32
#Mann= 3 , 0 , 0
       0      .1       0     352    .045       0   391.1     .06       0
Bank Sta=352,391.1
XS Rating Curve= 0 ,0
Exp/Cntr=0.3,0.1

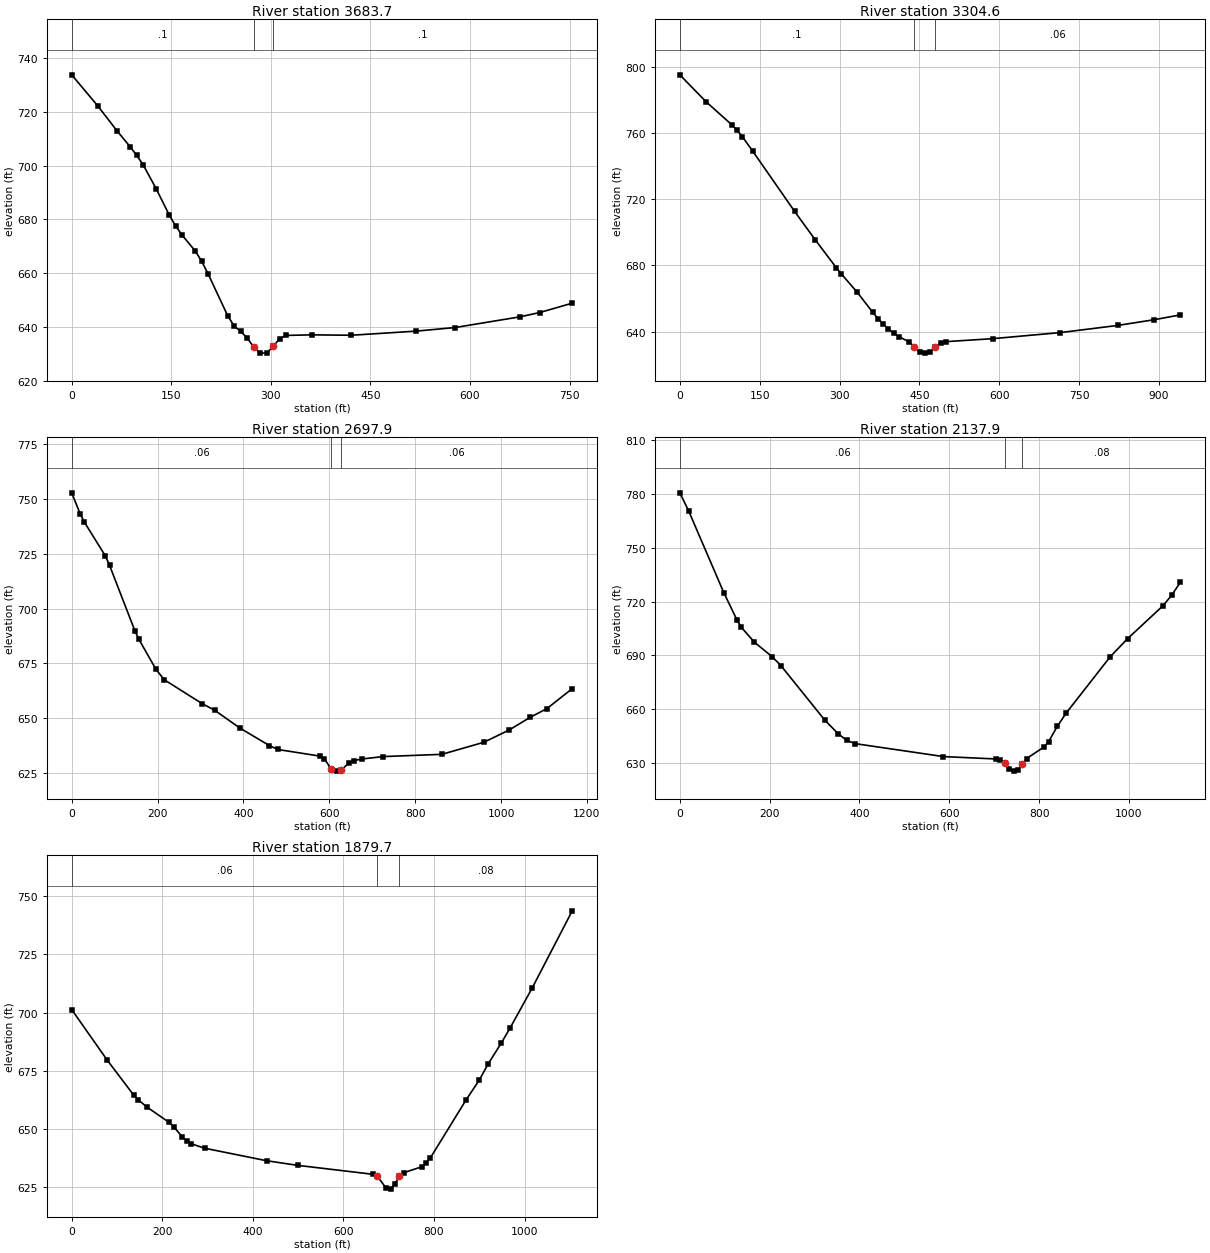
Type RM Length L Ch R = 1 ,3683.7  ,377.8,379.1,380.6
XS GIS Cut Line= 2
     1682571.403      485925.741     1683198.343      486344.724
#Sta/Elev= 30
       0  733.69    39.2  722.18    68.6  712.78    88.1  706.95    97.9  703.79
   107.7  700.25   127.3  691.35   146.9  681.62   156.7  677.53   166.5  674.08
   186.1  668.27   195.9   664.4   205.6  659.69     235   644.2   244.8  640.36
   254.6  638.34   264.4  635.92   274.2  632.61     284  630.33   293.8   630.3
   303.6   632.8   313.4  635.72   323.2  636.88   362.3  637.09   421.1  636.94
     519  638.47   577.8  639.82   675.7   643.8   705.1  645.38   754.1  648.86
#Mann= 3 , 0 , 0
       0      .1       0   274.2    .045       0   303.6      .1       0
Bank Sta=274.2,303.6
XS Rating Curve= 0 ,0
Exp/Cntr=0.3,0.1

Type RM Length L Ch R = 1 ,3304.6  ,599.3,606.7,614.8
XS GIS Cut Line= 2
     1682260.037      486136.351     1683008.322      486705.411
#Sta/Elev= 30
       0  795.35      49  779.14    97.9  765.04   107.7   761.7   117.5  757.85
   137.1  749.08   215.4  712.78   254.6  695.38   293.8  678.66   303.6  674.75
     333  663.84   362.3  651.63   372.1  647.85   381.9   644.5   391.7  641.55
   401.5  638.99   411.3  636.98   430.9  633.66   440.7  630.74   450.5  627.75
   460.2  626.95     470  627.81   479.8  630.45   489.6  632.96   499.4  633.89
   587.6   635.7   714.9  639.39   822.6  643.72   891.1  647.18   940.1  650.09
#Mann= 3 , 0 , 0
       0      .1       0   440.7    .045       0   479.8     .06       0
Bank Sta=440.7,479.8
XS Rating Curve= 0 ,0
Exp/Cntr=0.3,0.1

Type RM Length L Ch R = 1 ,2697.9  ,559.8,560,559.2
XS GIS Cut Line= 2
     1681899.503      486365.973     1682544.159      487337.297
#Sta/Elev= 30
       0  752.74    19.6  743.24    29.4  739.43    78.4     724    88.2  719.69
     147  689.98   156.7  685.94   195.9  672.44   215.5  667.59   303.7  656.72
   333.1  653.67   391.9  645.56   460.4   637.6     480  635.81     578   632.8
   587.8  631.69     604  627.11   607.4  626.24   617.2  625.95   626.6626.2475
   646.6   629.8   656.4  630.72     676  631.48   724.9  632.57   862.1   633.6
   960.1   639.1  1018.8  644.68  1067.8  650.46    1107  654.46  1165.8  663.54
#Mann= 3 , 0 , 0
       0     .06       0     604    .045       0   626.6     .06       0
Bank Sta=604,626.6
XS Rating Curve= 0 ,0
Exp/Cntr=0.3,0.1

Type RM Length L Ch R = 1 ,2137.9  ,267.4,258.2,249
XS GIS Cut Line= 2
     1681439.076      486659.215     1682062.223      487583.411
#Sta/Elev= 30
       0  780.74    19.6  770.63    97.8  725.04   127.1   709.8   136.9  705.64
   166.2  697.28   205.3  689.26   224.9  684.28   322.7  653.82     352  646.32
   371.6  642.47   391.1  640.64   586.7  633.44     704   632.1   713.8  631.72
   723.6  629.85   733.3  626.62     743  625.31   752.9  626.05   762.7  629.16
   772.4  632.36   811.6  638.93   821.3  641.82   840.9  650.49   860.4  657.78
   958.2  689.15   997.3  699.35  1075.5   717.6  1095.1  723.49  1114.6  730.84
#Mann= 3 , 0 , 0
       0     .06       0   723.6    .045       0   762.7     .08       0
Bank Sta=723.6,762.7
XS Rating Curve= 0 ,0
Exp/Cntr=0.3,0.1

Type RM Length L Ch R = 1 ,1879.7  ,167.7,161.1,160.9
XS GIS Cut Line= 2
     1681090.735       487088.01      1682020.48      487685.676
#Sta/Elev= 30
       0  701.34    78.2   679.7   136.9  664.62   146.7  662.64   166.3  659.48
   215.2   652.9     225  651.07   244.5  646.66   254.3  644.96   264.1  643.73
   293.4  641.83   430.4  636.45   498.8  634.47   665.1  630.63   674.9  629.78
   694.5  624.63   704.2  624.26     714  626.66   723.8  629.76   733.6  631.34
   772.7  633.83   782.5  635.32   792.3  637.75   870.5  662.45   899.9  671.05
   919.4  677.93   948.8  687.03   968.3  693.52  1017.2  710.72  1105.3  743.73
#Mann= 3 , 0 , 0
       0     .06       0   674.9    .045       0   723.8     .08       0
Bank Sta=674.9,723.8
XS Rating Curve= 0 ,0
Exp/Cntr=0.3,0.1