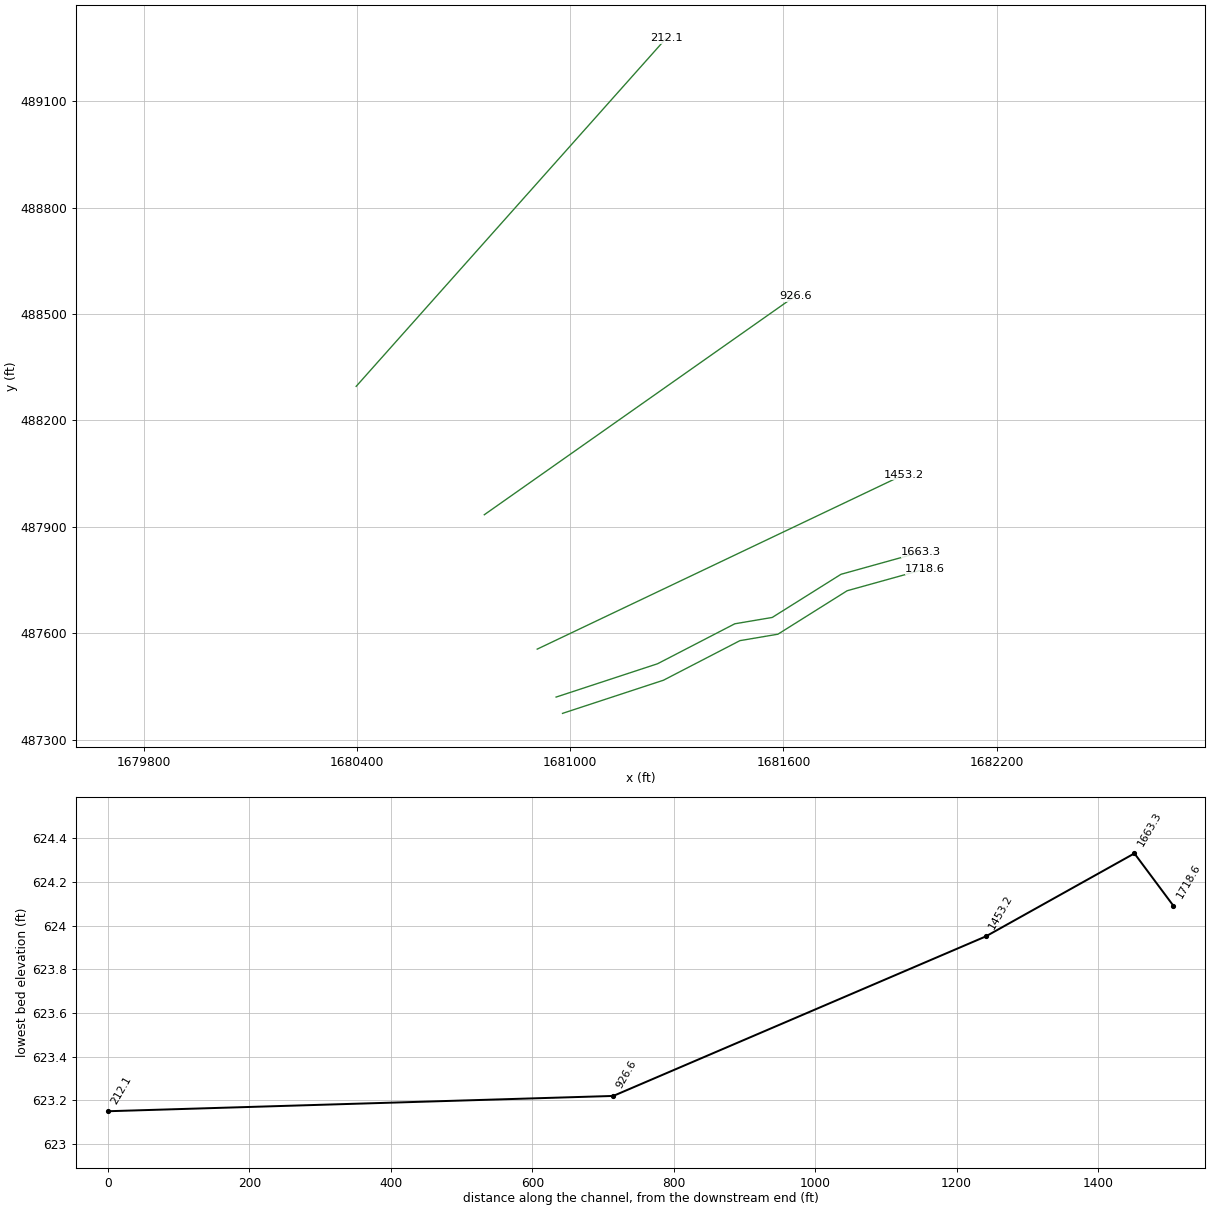
HEC-RAS study ClymerCk.prj: ClymerCk

--- ClymerCk.g01 (geometry) --- (continued)

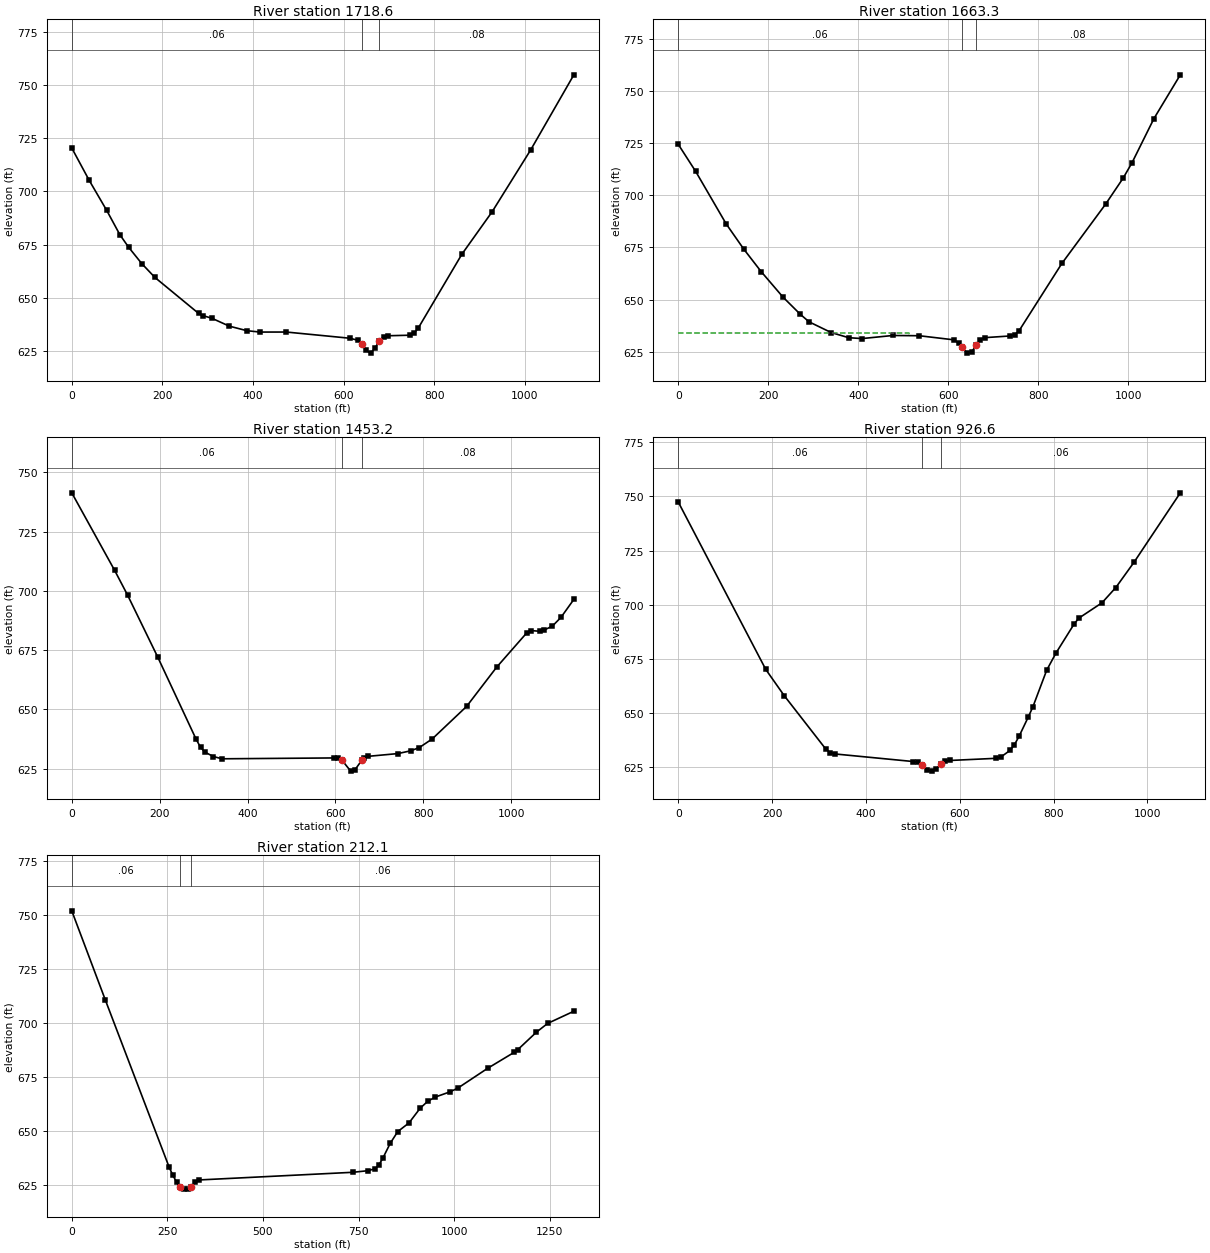
Type RM Length L Ch R = 1 ,1718.6  ,59.4,55.2,49.3
XS GIS Cut Line= 6
     1680978.461      487373.768     1681262.598      487467.288
     1681477.725      487578.845     1681584.533      487596.986
     1681779.479      487719.591     1681998.962      487780.697
#Sta/Elev= 30
       0   720.4    38.6  705.16    77.2  691.06   106.1   679.7   125.4  673.82
   154.4  666.14   183.3  659.66   279.8  642.75   289.5  641.69   308.8  640.49
   347.6  636.76   386.4  634.62   415.4  633.98   473.6  633.99   613.7  631.08
   631.7  630.12   640.8  628.24   649.8  625.35   659.4  624.09     669  626.43
   678.6   629.8   688.2  631.79   697.8  632.25   745.8   632.5   755.4  633.46
     765  636.01   860.9  670.55   927.6  690.47    1013  719.63  1107.9  754.76
#Mann= 3 , 0 , 0
       0     .06       0   640.8    .045       0   678.6     .08       0
Bank Sta=640.8,678.6
XS Rating Curve= 0 ,0
Exp/Cntr=0.3,0.1

Type RM Length L Ch R = 1 ,1663.3  ,202.5,210.2,213.2
XS GIS Cut Line= 6
      1680960.41      487419.711     1681245.828      487513.651
     1681463.167      487626.356     1681568.589      487644.261
     1681762.058      487765.937     1681988.056      487828.857
#Sta/Elev= 30
       0  724.34    38.8  711.34   106.6  686.19   145.4   674.2   184.2  663.38
   232.6  651.19   271.4  642.88   290.8   639.3   339.6   634.2   378.8  631.72
   408.2   631.3   476.8  632.78   535.5  632.66   613.4  630.67   623.1  629.03
   629.8   627.1   642.5  624.33   652.2  624.98   661.8  628.07   671.3  630.85
   680.8  631.74   737.9  632.56   747.5  633.18     757  634.98   852.2  667.26
   949.2  695.61   988.3  708.12  1007.9  715.42  1056.7  736.63  1115.4  757.62
#Mann= 3 , 0 , 0
       0     .06       0   629.8    .045       0   661.8     .08       0
#XS Ineff= 2 , 0
          513.76  633.93
Permanent Ineff=
       F       F
Bank Sta=629.8,661.8
XS Rating Curve= 0 ,0
Exp/Cntr=0.3,0.1

Type RM Length L Ch R = 1 ,1453.2  ,521.9,526.6,530.9
XS GIS Cut Line= 2
     1680907.277      487554.943     1681938.706      488046.785
#Sta/Elev= 30
       0  741.31    97.7  708.56     127  698.19   195.3  672.18   283.2  637.32
     293  634.03   302.8  631.98   322.3  630.11   341.8  629.15   595.8  629.51
   605.5  629.44   615.3   628.5   634.8  623.95   644.6  624.54   660.3  628.58
   664.1  629.47   673.9  630.18   742.3  631.35   771.6  632.53   791.1   633.9
   820.4  637.53   898.5  651.22   966.9  667.76  1035.3  682.21    1045  683.24
  1064.6  682.92  1074.3  683.37  1093.9  685.12  1113.4  688.79  1142.7  696.37
#Mann= 3 , 0 , 0
       0     .06       0   615.3    .045       0   660.3     .08       0
Bank Sta=615.3,660.3
XS Rating Curve= 0 ,0
Exp/Cntr=0.3,0.1

Type RM Length L Ch R = 1 ,926.6   ,709.2,714.5,719.1
XS GIS Cut Line= 2
     1680758.391      487933.886     1681632.899      488550.421
#Sta/Elev= 30
       0  747.43   186.5  670.17   225.8  658.07   314.1   633.5   323.9  631.74
   333.8  631.15   500.6  627.65   510.4  627.26   520.3  625.86   530.1  623.78
   539.9  623.22   549.7  624.15   559.5  626.37   569.4  627.79   579.2  628.14
   677.3  629.13   687.2  629.67   706.8  632.74   716.6  635.45   726.4   639.3
     746   648.2   755.9  652.93   785.3  669.83     805  677.71   844.2  691.29
     854  693.86   903.1   700.9   932.6  707.96   971.8  719.75    1070  751.65
#Mann= 3 , 0 , 0
       0     .06       0   520.3    .045       0   559.5     .06       0
Bank Sta=520.3,559.5
XS Rating Curve= 0 ,0
Exp/Cntr=0.3,0.1

Type RM Length L Ch R = 1 ,212.1   ,202.4,212.1,221.8
XS GIS Cut Line= 2
      1680397.77      488295.825     1681269.947      489277.194
#Sta/Elev= 30
       0  751.98    88.2  710.51   254.8  633.23   264.6  629.46   274.3  626.37
   284.1     624   293.9  623.15   303.7  623.21   311.3  624.09   323.3  626.46
   333.1   627.4   734.8  630.94     774  631.67   793.6  632.61   803.4  634.44
   813.2   637.4   832.8  644.37   852.4  649.78   881.8   653.8   911.2  660.64
   930.8   663.8   950.4  665.76   989.6  668.22  1009.2  669.88  1087.6  679.09
  1156.2   686.4    1166  687.66    1215   695.8  1244.3  699.85  1312.9   705.5
#Mann= 3 , 0 , 0
       0     .06       0   284.1    .045       0   311.3     .06       0
Bank Sta=284.1,311.3
XS Rating Curve= 0 ,0
Exp/Cntr=0.3,0.1

Chan Stop Cuts=-1
Use User Specified Reach Order=0
Composite Channel Slope=5